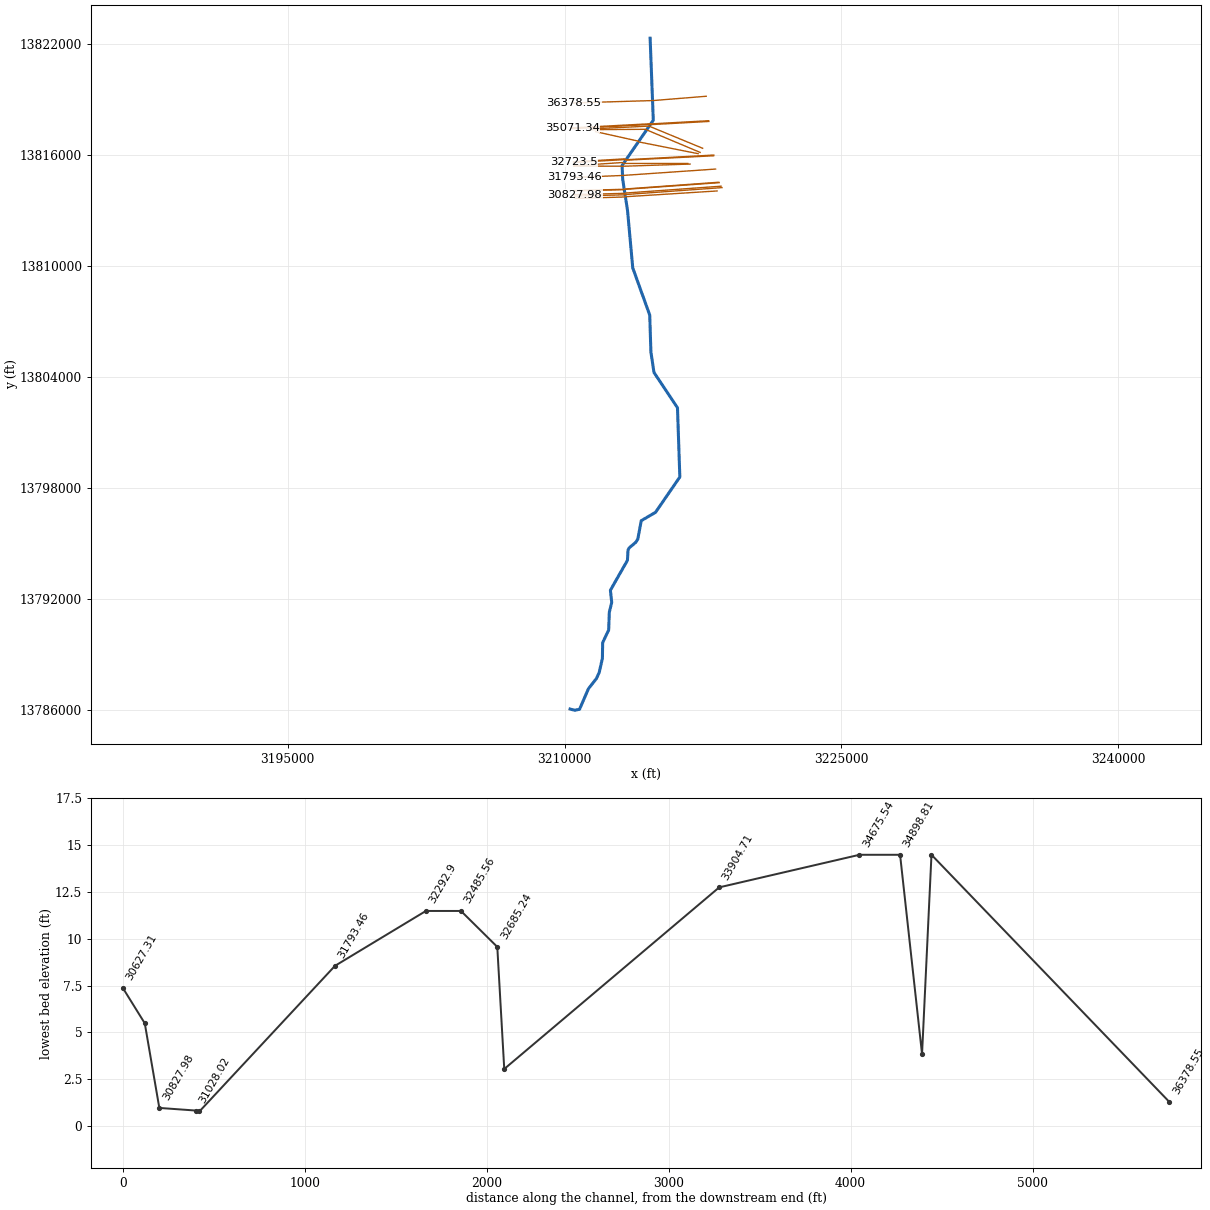
--- B106_00_00.prj (project) ---

Proj Title=B106-00-00
Current Plan=p03
Default Exp/Contr=.3,.1
English Units
Geom File=g03
Geom File=g02
Flow File=f03
Flow File=f02
Plan File=p03
Plan File=p02
Y Axis Title=Elevation
X Axis Title(PF)=Main Channel Distance
X Axis Title(XS)=Station
BEGIN DESCRIPTION:
Armand Bayou
Big Island Slough
HCFCD Unit B106-00-00
Flood Hazard Model
10, 2, 1, 0.2% Event
Filename B106_00_00.prj
Prepared by: Christopher Moss Date: 6/15/2004
Reviewd by:		Date:
Status FINAL
END DESCRIPTION:
DSS Export Rating Curves= 0
DSS Export Rating Curve Sorted= 0
DSS Export Volume Flow Curves= 0
DXF OffsetX= 0
DXF OffsetY= 0
DXF ScaleX= 1
DXF ScaleY= 10

--- B106_00_00.p03 (plan) ---

Plan Title=Floodway
Version=Version 3.0.1  Mar 2001
Short Identifier=Floodway0607
Geom File=g03
Flow File=f03
Subcritical Flow
K Sum by GR= 0
Std Step Tol= 0.01
Critical Tol= 0.01
Num of Std Step Trials= 20
Max Error Tol= 0.3
Flow Tol Ratio= 0.001
Split Flow NTrial= 30
Split Flow Tol= 0.02
Split Flow Ratio= 0.02
Log Output Level= 0
Friction Slope Method= 0
Unsteady Friction Slope Method= 2
Secant Critical Depth
Global Vel Dist= 0 , 0 , 0
Global Log Level= 0
CheckData=True
Encroach Param=-1 ,0,0, 2
Encroach River=B106-00-00
Encroach Reach=MAIN
Encroach Node=36378.55
       1 4886.51 5121.09
Encroach Node=35071.34
       1 4822.78 5158.55
Encroach Node=35019.49
       1 4948.78 5116.15
Encroach Node=34959.15
       1 4948.78 5116.15
Encroach Node=34898.81
       1 4830.25    5065
Encroach Node=34675.54
       1 4948.78 5051.22
Encroach Node=33904.71
       1 4901.29 5149.73
Encroach Node=32723.5
       1 4924.72 5039.72
Encroach Node=32685.24
       1 4891.72 5039.72
Encroach Node=32585.4
       1 4891.72 5039.72
Encroach Node=32485.56
       1 4935.59 5054.72
Encroach Node=32292.9
       1 4891.44 5039.76
Encroach Node=31793.46
       1 4887.39 5076.73
Encroach Node=31048.03
       1 4877.47 5060.62
Encroach Node=31028.02
       1 4872.63 5055.29
Encroach Node=30827.98
       1 4920.44 5046.91
Encroach Node=30747.98
       1 4874.29    5050
Encroach Node=30627.31
       1 4932.42 5050.81
Encroach Node=29590.01
       1 4927.25 5054.22
Encroach Node=28463.24
       1 4934.45 5065.55
Encroach Node=27399.88
       1 4933.34 5107.56
Encroach Node=27004.57
       1    4967 5086.39
Encroach Node=26964.57
       1 4928.55 5156.57
Encroach Node=26863.5
       1 4928.55 5156.57
Encroach Node=26762.42
       1 4928.55 5156.57
Encroach Node=26562.23
       1  4927.4 5083.29
Encroach Node=26226.91
       1 4871.88 5080.94
Encroach Node=26216.9
       1 4877.27 5140.79
Encroach Node=26166.84
       1 4877.27 5140.79
Encroach Node=26116.78
       1 4922.29    5050
Encroach Node=26075.36
       1 4914.17 5080.94
Encroach Node=24973.02
       1 4910.56    5062
Encroach Node=24933.01
       1 4907.14 5073.01
Encroach Node=24855.82
       1 4907.14 5073.01
Encroach Node=24778.62
       1 4908.89 5073.01
Encroach Node=24597.37
       1 4911.62 5073.01
Encroach Node=23766.16
       1 4890.85 5084.45
Encroach Node=23079.37
       1 4925.25 5109.42
Encroach Node=22360.17
       1  4926.7    5062
Encroach Node=22259.92
       1 4855.64 5163.25
Encroach Node=22049.1
       1 4855.64 5163.25
Encroach Node=21838.21
       1 4855.64 5163.25
Encroach Node=21441.61
       1 4816.88  5085.8
Encroach Node=20735.69
       1 4832.24 5082.78
Encroach Node=19794.28
       1 4924.51 5091.63
Encroach Node=18685.77
       1 4837.14 5101.35
Encroach Node=17927.3
       1 4820.47 5075.34
Encroach Node=17421.75
       1 4813.36 5080.99
Encroach Node=17381.61
       1 4862.38 5085.99
Encroach Node=17298.1
       1 4862.38 5085.99
Encroach Node=17214.6
       1 4894.53    5123
Encroach Node=17053.81
       1 4829.73 5085.99
Encroach Node=15961.79
       1 4881.12 5137.26
Encroach Node=15951.73
       1 4880.52    5105
Encroach Node=15851.44
       1 4895.01  5118.4
Encroach Node=15812.37
       1 4889.35 5142.35
Encroach Node=14880.77
       1 4886.98 5113.02
Encroach Node=13669.39
       1 4833.04 5087.95
Encroach Node=12815.75
       1 4903.55  5155.9
Encroach Node=12003.06
       1 4842.13  5092.4
Encroach Node=11534.3
       1  4874.2 5090.98
Encroach Node=10505.78
       1 4854.66 5103.25
Encroach Node=10495.47
       1 4857.35 5103.25
Encroach Node=10272.1
       1  4885.8  5083.4
Encroach Node=10048.67
       1  4885.8  5083.4
Encroach Node=9989.7
       1  4921.6    5117
Encroach Node=9930.678
       1  4921.6    5117
Encroach Node=9890.046
       1    4913    5098
Encroach Node=8433.446
       1  4750.9 5205.04
Encroach Node=7639.533
       1 4830.41 5102.76
Encroach Node=6580.048
       1 4705.02 5240.37
Encroach Node=6533.497
       1 4615.05 5393.06
Encroach Node=6273.6
       1 4912.43 5088.85
Encroach Node=6013.685
       1 4713.49 5203.66
Encroach Node=5837.123
       1 4884.14 5128.93
Encroach Node=5280.757
       1 4572.97 5109.67
Encroach Node=4511.779
       1 4888.72 5273.36
Encroach Node=2969.15
       1 4661.85 5621.23
Encroach Reach=B106-00-00_0030
Encroach Node=36378.55
       1 4886.51 5121.09
Encroach Node=35071.34
       1 4822.78 5158.55
Encroach Node=35019.49
       1 4948.78 5116.15
Encroach Node=34959.15
       1 4948.78 5116.15
Encroach Node=34898.81
       1 4830.25    5065
Encroach Node=34675.54
       1 4948.78 5051.22
Encroach Node=33904.71
       1 4901.29 5149.73
Encroach Node=32723.5
       1 4924.72 5039.72
Encroach Node=32685.24
       1 4891.72 5039.72
Encroach Node=32585.4
       1 4891.72 5039.72
Encroach Node=32485.56
       1 4935.59 5054.72
Encroach Node=32292.9
       1 4891.44 5039.76
Encroach Node=31793.46
       1 4887.39 5076.73
Encroach Node=31048.03
       1 4877.47 5060.62
Encroach Node=31028.02
       1 4872.63 5055.29
Encroach Node=30827.98
       1 4920.44 5046.91
Encroach Node=30747.98
       1 4874.29    5050
Encroach Node=30627.31
       1 4932.42 5050.81
Encroach Node=29590.01
       1 4927.25 5054.22
Encroach Node=28463.24
       1 4934.45 5065.55
Encroach Node=27399.88
       1 4933.34 5107.56
Encroach Node=27004.57
       1    4967 5086.39
Encroach Node=26964.57
       1 4928.55 5156.57
Encroach Node=26863.5
       1 4928.55 5156.57
Encroach Node=26762.42
       1 4928.55 5156.57
Encroach Node=26562.23
       1  4927.4 5083.29
Encroach Node=26226.91
       1 4871.88 5080.94
Encroach Node=26216.9
       1 4877.27 5140.79
Encroach Node=26166.84
       1 4877.27 5140.79
Encroach Node=26116.78
       1 4922.29    5050
Encroach Node=26075.36
       1 4914.17 5080.94
Encroach Node=24973.02
       1 4910.56    5062
Encroach Node=24933.01
       1 4907.14 5073.01
Encroach Node=24855.82
       1 4907.14 5073.01
Encroach Node=24778.62
       1 4908.89 5073.01
Encroach Node=24597.37
       1 4911.62 5073.01
Encroach Node=23766.16
       1 4890.85 5084.45
Encroach Node=23079.37
       1 4925.25 5109.42
Encroach Node=22360.17
       1  4926.7    5062
Encroach Node=22259.92
       1 4855.64 5163.25
Encroach Node=22049.1
       1 4855.64 5163.25
Encroach Node=21838.21
       1 4855.64 5163.25
Encroach Node=21441.61
       1 4816.88  5085.8
Encroach Node=20735.69
       1 4832.24 5082.78
Encroach Node=19794.28
       1 4924.51 5091.63
Encroach Node=18685.77
       1 4837.14 5101.35
Encroach Node=17927.3
       1 4820.47 5075.34
Encroach Node=17421.75
       1 4813.36 5080.99
Encroach Node=17381.61
       1 4862.38 5085.99
Encroach Node=17298.1
       1 4862.38 5085.99
Encroach Node=17214.6
       1 4894.53    5123
Encroach Node=17053.81
       1 4829.73 5085.99
Encroach Node=15961.79
       1 4881.12 5137.26
Encroach Node=15951.73
       1 4880.52    5105
Encroach Node=15851.44
       1 4895.01  5118.4
Encroach Node=15812.37
       1 4889.35 5142.35
Encroach Node=14880.77
       1 4886.98 5113.02
Encroach Node=13669.39
       1 4833.04 5087.95
Encroach Node=12815.75
       1 4903.55  5155.9
Encroach Node=12003.06
       1 4842.13  5092.4
Encroach Node=11534.3
       1  4874.2 5090.98
Encroach Node=10505.78
       1 4854.66 5103.25
Encroach Node=10495.47
       1 4857.35 5103.25
Encroach Node=10272.1
       1  4885.8  5083.4
Encroach Node=10048.67
       1  4885.8  5083.4
Encroach Node=9989.7
       1  4921.6    5117
Encroach Node=9930.678
       1  4921.6    5117
Encroach Node=9890.046
       1    4913    5098
Encroach Node=8433.446
       1  4750.9 5205.04
Encroach Node=7639.533
       1 4830.41 5102.76
Encroach Node=6580.048
       1 4705.02 5240.37
Encroach Node=6533.497
       1 4615.05 5393.06
Encroach Node=6273.6
       1 4912.43 5088.85
Encroach Node=6013.685
       1 4713.49 5203.66
Encroach Node=5837.123
       1 4884.14 5128.93
Encroach Node=5280.757
       1 4572.97 5109.67
Encroach Node=4511.779
       1 4888.72 5273.36
Encroach Node=2969.15
       1 4661.85 5621.23
Computation Interval=1HOUR
Output Interval=1HOUR
Run HTab= 0
Run UNet= 0
Run PostProcess= 0
UNET Theta= 1
UNET ZTol= 0.02
UNET ZSATol= 0.1
UNET MxIter= 20
UNET MaxInSteps= 20
UNET DtIC= 0
UNET DtMin= 0
UNET MaxCRTS= 20
UNET WFStab= 2
UNET SFStab= 1
UNET WFX= 1
UNET SFX= 1
UNET Convert EG Bridges=-1
UNET Use Existing IB Tables=-1
Instantaneous Interval=1HOUR
Write IC File= 0
IC Time=0
Write Velocity= 0
Write Detailed= 0

--- B106_00_00.p02 (plan) ---

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Plan Title=FEMA Effective June 2007
Short Identifier=FEMAeff0607
Geom File=g02
Flow File=f02
Encroach Param=-1 ,0,0, 0
DSS File=dss

--- B106_00_00.f03 (steady flow) ---

Flow Title=Floodway
Version=Version 3.0.1  Mar 2001
Number of Profiles= 2
Profile Names=1PCT_100yr, 1PCTFloodway_100yrFW
River Rch & RM=Big Island,Main            ,36378.55
     854     854
River Rch & RM=Big Island,Main            ,35071.34
     871     871
River Rch & RM=Big Island,Main            ,34675.54
     903     903
River Rch & RM=Big Island,Main            ,33904.71
    1194    1194
River Rch & RM=Big Island,Main            ,32723.5
    1205    1205
River Rch & RM=Big Island,Main            ,32685.24
    1293    1293
River Rch & RM=Big Island,Main            ,32485.56
    1385    1385
River Rch & RM=Big Island,Main            ,32292.9
    1490    1490
River Rch & RM=Big Island,Main            ,31793.46
    1661    1661
River Rch & RM=Big Island,Main            ,31048.03
    1716    1716
River Rch & RM=Big Island,Main            ,30827.98
    1767    1767
River Rch & RM=Big Island,Main            ,30627.31
    2057    2057
River Rch & RM=Big Island,Main            ,29590.01
    2426    2426
River Rch & RM=Big Island,Main            ,28463.24
    2835    2835
River Rch & RM=Big Island,Main            ,27399.88
    3003    3003
River Rch & RM=Big Island,Main            ,27004.57
    3112    3112
River Rch & RM=Big Island,Main            ,26762.42
    3264    3264
River Rch & RM=Big Island,Main            ,26216.9
    3304    3304
River Rch & RM=Big Island,Main            ,26075.36
    3638    3638
River Rch & RM=Big Island,Main            ,24973.02
    3759    3759
River Rch & RM=Big Island,Main            ,24597.37
    4042    4042
River Rch & RM=Big Island,Main            ,23766.16
    4292    4292
River Rch & RM=Big Island,Main            ,23079.37
    4570    4570
River Rch & RM=Big Island,Main            ,22360.17
    4610    4610
River Rch & RM=Big Island,Main            ,22259.92
    4783    4783
River Rch & RM=Big Island,Main            ,21838.21
    4897    4897
River Rch & RM=Big Island,Main            ,20735.69
    4996    4996
River Rch & RM=Big Island,Main            ,19794.28
    5116    5116
River Rch & RM=Big Island,Main            ,18685.77
    5279    5279
River Rch & RM=Big Island,Main            ,17214.6
    5422    5422
River Rch & RM=Big Island,Main            ,15961.79
    5548    5548
River Rch & RM=Big Island,Main            ,14880.77
    5694    5694
River Rch & RM=Big Island,Main            ,13669.39
    5798    5798
River Rch & RM=Big Island,Main            ,12815.75
    5959    5959
River Rch & RM=Big Island,Main            ,11534.3
    6093    6093
River Rch & RM=Big Island,Main            ,10495.47
    6166    6166
River Rch & RM=Big Island,Main            ,9930.678
    6412    6412
River Rch & RM=Big Island,Main            ,5837.123
    6590    6590
River Rch & RM=B106-00-00,B106-00-00_0030            ,36378.55
     854     854
River Rch & RM=B106-00-00,B106-00-00_0030            ,35071.34
     871     871
River Rch & RM=B106-00-00,B106-00-00_0030            ,34675.54
     903     903
River Rch & RM=B106-00-00,B106-00-00_0030            ,33904.71
    1194    1194
River Rch & RM=B106-00-00,B106-00-00_0030            ,32723.5
    1205    1205
River Rch & RM=B106-00-00,B106-00-00_0030            ,32685.24
    1293    1293
River Rch & RM=B106-00-00,B106-00-00_0030            ,32485.56
    1385    1385
River Rch & RM=B106-00-00,B106-00-00_0030            ,32292.9
    1490    1490
River Rch & RM=B106-00-00,B106-00-00_0030            ,31793.46
    1661    1661
River Rch & RM=B106-00-00,B106-00-00_0030            ,31048.03
    1716    1716
River Rch & RM=B106-00-00,B106-00-00_0030            ,30827.98
    1767    1767
River Rch & RM=B106-00-00,B106-00-00_0030            ,30627.31
    2057    2057
River Rch & RM=B106-00-00,B106-00-00_0030            ,29590.01
    2426    2426
River Rch & RM=B106-00-00,B106-00-00_0030            ,28463.24
    2835    2835
River Rch & RM=B106-00-00,B106-00-00_0030            ,27399.88
    3003    3003
River Rch & RM=B106-00-00,B106-00-00_0030            ,27004.57
    3112    3112
River Rch & RM=B106-00-00,B106-00-00_0030            ,26762.42
    3264    3264
River Rch & RM=B106-00-00,B106-00-00_0030            ,26216.9
    3304    3304
River Rch & RM=B106-00-00,B106-00-00_0030            ,26075.36
    3638    3638
River Rch & RM=B106-00-00,B106-00-00_0030            ,24973.02
    3759    3759
River Rch & RM=B106-00-00,B106-00-00_0030            ,24597.37
    4042    4042
River Rch & RM=B106-00-00,B106-00-00_0030            ,23766.16
    4292    4292
River Rch & RM=B106-00-00,B106-00-00_0030            ,23079.37
    4570    4570
River Rch & RM=B106-00-00,B106-00-00_0030            ,22360.17
    4610    4610
River Rch & RM=B106-00-00,B106-00-00_0030            ,22259.92
    4783    4783
River Rch & RM=B106-00-00,B106-00-00_0030            ,21838.21
    4897    4897
River Rch & RM=B106-00-00,B106-00-00_0030            ,20735.69
    4996    4996
River Rch & RM=B106-00-00,B106-00-00_0030            ,19794.28
    5116    5116
River Rch & RM=B106-00-00,B106-00-00_0030            ,18685.77
    5279    5279
River Rch & RM=B106-00-00,B106-00-00_0030            ,17214.6
    5422    5422
River Rch & RM=B106-00-00,B106-00-00_0030            ,15961.79
    5548    5548
River Rch & RM=B106-00-00,B106-00-00_0030            ,14880.77
    5694    5694
River Rch & RM=B106-00-00,B106-00-00_0030            ,13669.39
    5798    5798
River Rch & RM=B106-00-00,B106-00-00_0030            ,12815.75
    5959    5959
River Rch & RM=B106-00-00,B106-00-00_0030            ,11534.3
    6093    6093
River Rch & RM=B106-00-00,B106-00-00_0030            ,10495.47
    6166    6166
River Rch & RM=B106-00-00,B106-00-00_0030            ,9930.678
    6412    6412
River Rch & RM=B106-00-00,B106-00-00_0030            ,5837.123
    6590    6590
Boundary for River Rch & Prof#=B106-00-00,B106-00-00_0030            , 1
Up Type= 0
Dn Type= 3
Dn Slope=.00046
Boundary for River Rch & Prof#=B106-00-00,B106-00-00_0030            , 2
Up Type= 0
Dn Type= 3
Dn Slope=.00046
DSS Import GetInterval= 0
DSS Import GetPeak= 0
DSS Import FillOption= 0

--- B106_00_00.f02 (steady flow) ---

Flow Title=FEMA Effective June 2007
Version=Version 3.0.1  Mar 2001
Number of Profiles= 4
Profile Names=10PCT_10yr, 2PCT_50yr, 1PCT_100yr, 0.2PCT_500yr
River Rch & RM=Big Island,Main            ,36378.55
     498     733     854    1207
River Rch & RM=Big Island,Main            ,35071.34
     508     747     871    1230
River Rch & RM=Big Island,Main            ,34675.54
     527     774     903    1275
River Rch & RM=Big Island,Main            ,33904.71
     697    1024    1194    1687
River Rch & RM=Big Island,Main            ,32723.5
     703    1033    1205    1702
River Rch & RM=Big Island,Main            ,32685.24
     754    1109    1293    1827
River Rch & RM=Big Island,Main            ,32485.56
     807    1187    1385    1956
River Rch & RM=Big Island,Main            ,32292.9
     871    1278    1490    2100
River Rch & RM=Big Island,Main            ,31793.46
     974    1425    1661    2336
River Rch & RM=Big Island,Main            ,31048.03
    1007    1472    1716    2411
River Rch & RM=Big Island,Main            ,30827.98
    1038    1516    1767    2481
River Rch & RM=Big Island,Main            ,30627.31
    1213    1765    2057    2877
River Rch & RM=Big Island,Main            ,29590.01
    1438    2083    2426    3380
River Rch & RM=Big Island,Main            ,28463.24
    1688    2435    2835    3934
River Rch & RM=Big Island,Main            ,27399.88
    1791    2580    3003    4163
River Rch & RM=Big Island,Main            ,27004.57
    1858    2673    3112    4309
River Rch & RM=Big Island,Main            ,26762.42
    1953    2813    3264    4497
River Rch & RM=Big Island,Main            ,26216.9
    1979    2850    3304    4547
River Rch & RM=Big Island,Main            ,26075.36
    2190    3158    3638    4955
River Rch & RM=Big Island,Main            ,24973.02
    2267    3270    3759    5103
River Rch & RM=Big Island,Main            ,24597.37
    2448    3533    4042    5445
River Rch & RM=Big Island,Main            ,23766.16
    2607    3766    4292    5745
River Rch & RM=Big Island,Main            ,23079.37
    2786    4026    4570    6077
River Rch & RM=Big Island,Main            ,22360.17
    2811    4064    4610    6124
River Rch & RM=Big Island,Main            ,22259.92
    2923    4226    4783    6329
River Rch & RM=Big Island,Main            ,21838.21
    2985    4321    4897    6482
River Rch & RM=Big Island,Main            ,20735.69
    3040    4404    4996    6614
River Rch & RM=Big Island,Main            ,19794.28
    3106    4503    5116    6774
River Rch & RM=Big Island,Main            ,18685.77
    3195    4638    5279    6992
River Rch & RM=Big Island,Main            ,17214.6
    3273    4757    5422    7184
River Rch & RM=Big Island,Main            ,15961.79
    3342    4861    5548    7353
River Rch & RM=Big Island,Main            ,14880.77
    3421    4981    5694    7548
River Rch & RM=Big Island,Main            ,13669.39
    3478    5067    5798    7688
River Rch & RM=Big Island,Main            ,12815.75
    3565    5200    5959    7903
River Rch & RM=Big Island,Main            ,11534.3
    3637    5309    6093    8082
River Rch & RM=Big Island,Main            ,10495.47
    3676    5370    6166    8181
River Rch & RM=Big Island,Main            ,9930.678
    3825    5573    6412    8483
River Rch & RM=Big Island,Main            ,5837.123
    3932    5720    6590    8702
River Rch & RM=B106-00-00,B106-00-00_0030            ,36378.55
     498     733     854    1207
River Rch & RM=B106-00-00,B106-00-00_0030            ,35071.34
     508     747     871    1230
River Rch & RM=B106-00-00,B106-00-00_0030            ,34675.54
     527     774     903    1275
River Rch & RM=B106-00-00,B106-00-00_0030            ,33904.71
     697    1024    1194    1687
River Rch & RM=B106-00-00,B106-00-00_0030            ,32723.5
     703    1033    1205    1702
River Rch & RM=B106-00-00,B106-00-00_0030            ,32685.24
     754    1109    1293    1827
River Rch & RM=B106-00-00,B106-00-00_0030            ,32485.56
     807    1187    1385    1956
River Rch & RM=B106-00-00,B106-00-00_0030            ,32292.9
     871    1278    1490    2100
River Rch & RM=B106-00-00,B106-00-00_0030            ,31793.46
     974    1425    1661    2336
River Rch & RM=B106-00-00,B106-00-00_0030            ,31048.03
    1007    1472    1716    2411
River Rch & RM=B106-00-00,B106-00-00_0030            ,30827.98
    1038    1516    1767    2481
River Rch & RM=B106-00-00,B106-00-00_0030            ,30627.31
    1213    1765    2057    2877
River Rch & RM=B106-00-00,B106-00-00_0030            ,29590.01
    1438    2083    2426    3380
River Rch & RM=B106-00-00,B106-00-00_0030            ,28463.24
    1688    2435    2835    3934
River Rch & RM=B106-00-00,B106-00-00_0030            ,27399.88
    1791    2580    3003    4163
River Rch & RM=B106-00-00,B106-00-00_0030            ,27004.57
    1858    2673    3112    4309
River Rch & RM=B106-00-00,B106-00-00_0030            ,26762.42
    1953    2813    3264    4497
River Rch & RM=B106-00-00,B106-00-00_0030            ,26216.9
    1979    2850    3304    4547
River Rch & RM=B106-00-00,B106-00-00_0030            ,26075.36
    2190    3158    3638    4955
River Rch & RM=B106-00-00,B106-00-00_0030            ,24973.02
    2267    3270    3759    5103
River Rch & RM=B106-00-00,B106-00-00_0030            ,24597.37
    2448    3533    4042    5445
River Rch & RM=B106-00-00,B106-00-00_0030            ,23766.16
    2607    3766    4292    5745
River Rch & RM=B106-00-00,B106-00-00_0030            ,23079.37
    2786    4026    4570    6077
River Rch & RM=B106-00-00,B106-00-00_0030            ,22360.17
    2811    4064    4610    6124
River Rch & RM=B106-00-00,B106-00-00_0030            ,22259.92
    2923    4226    4783    6329
River Rch & RM=B106-00-00,B106-00-00_0030            ,21838.21
    2985    4321    4897    6482
River Rch & RM=B106-00-00,B106-00-00_0030            ,20735.69
    3040    4404    4996    6614
River Rch & RM=B106-00-00,B106-00-00_0030            ,19794.28
    3106    4503    5116    6774
River Rch & RM=B106-00-00,B106-00-00_0030            ,18685.77
    3195    4638    5279    6992
River Rch & RM=B106-00-00,B106-00-00_0030            ,17214.6
    3273    4757    5422    7184
River Rch & RM=B106-00-00,B106-00-00_0030            ,15961.79
    3342    4861    5548    7353
River Rch & RM=B106-00-00,B106-00-00_0030            ,14880.77
    3421    4981    5694    7548
River Rch & RM=B106-00-00,B106-00-00_0030            ,13669.39
    3478    5067    5798    7688
River Rch & RM=B106-00-00,B106-00-00_0030            ,12815.75
    3565    5200    5959    7903
River Rch & RM=B106-00-00,B106-00-00_0030            ,11534.3
    3637    5309    6093    8082
River Rch & RM=B106-00-00,B106-00-00_0030            ,10495.47
    3676    5370    6166    8181
River Rch & RM=B106-00-00,B106-00-00_0030            ,9930.678
    3825    5573    6412    8483
River Rch & RM=B106-00-00,B106-00-00_0030            ,5837.123
    3932    5720    6590    8702
Boundary for River Rch & Prof#=B106-00-00,B106-00-00_0030            , 1
Up Type= 0
Dn Type= 3
Dn Slope=.00046
Boundary for River Rch & Prof#=B106-00-00,B106-00-00_0030            , 2
Up Type= 0
Dn Type= 3
Dn Slope=.00046
Boundary for River Rch & Prof#=B106-00-00,B106-00-00_0030            , 3
Up Type= 0
Dn Type= 3
Dn Slope=.00046
Boundary for River Rch & Prof#=B106-00-00,B106-00-00_0030            , 4
Up Type= 0
Dn Type= 3
Dn Slope=.00046
DSS Import GetInterval= 0
DSS Import GetPeak= 0
DSS Import FillOption= 0

--- B106_00_00.g03 (geometry) ---

Geom Title=B106-00-00 June 2007 (Floodway)
Version=Version 3.0.1  Mar 2001

River Reach=B106-00-00      ,B106-00-00_0030
Reach XY= 30
      3214637.25       13822329.       3214809.5       13817893.
       3213118.5       13815448.      3213150.25       13814704.
      3213412.75       13813014.      3213695.75       13809909.
        3214616.       13807356.        3214680.       13805357.
      3214845.75       13804256.      3216120.25       13802343.
       3216247.5       13798602.       3214930.5       13796692.
      3214156.75       13796239.       3213968.5       13795241.
       3213856.5       13795068.        3213500.       13794768.
        3213439.       13794651.       3213408.5       13794096.
      3212484.75       13792479.        3212556.       13791820.
        3212426.       13791289.      3212390.75       13790328.
      3212065.25       13789647.      3212051.25       13788797.
      3211878.25       13788033.        3211728.       13787706.
      3211294.25       13787154.      3210812.25       13786041.
       3210549.5       13785989.      3210300.25       13786054.

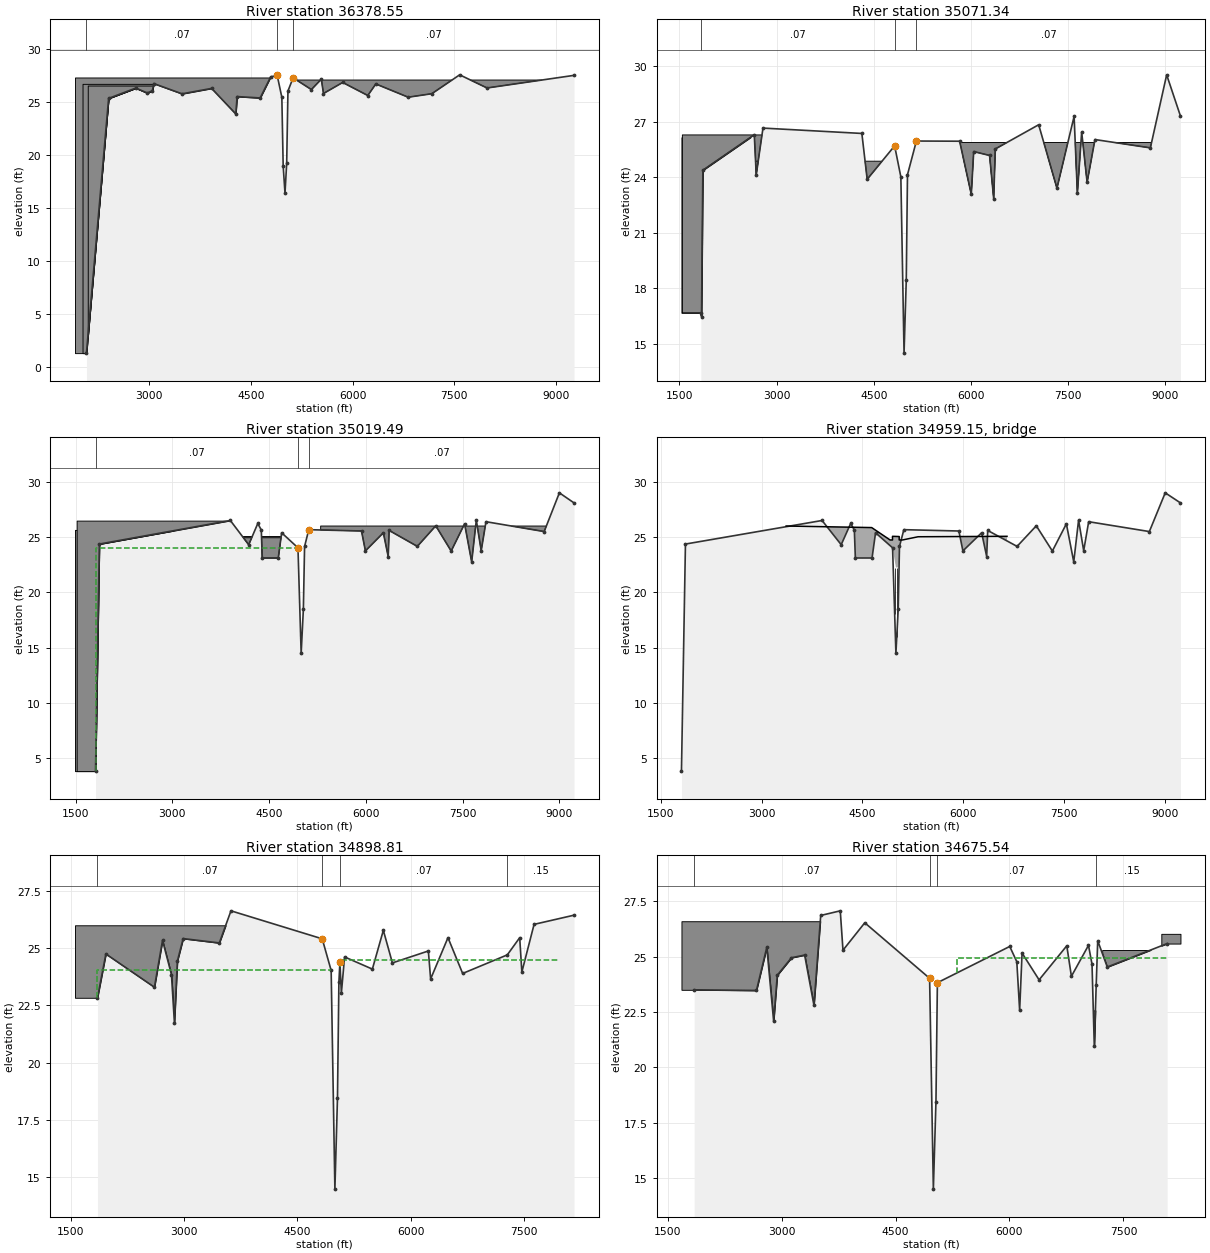
Type RM Length L Ch R = 1 ,36378.55,1270.33,1307.21,1346.67
XS GIS Cut Line= 4
     3217677.984    13819188.535     3214804.913    13818956.975
     3214714.827    13818954.472     3210495.559    13818828.217
#Sta/Elev= 30
 2072.18    1.29  2399.3    25.3 2800.33   26.27 2970.08   25.81 3045.15   26.02
 3064.37    26.7 3482.67   25.73 3918.61   26.24  4275.1   23.83  4295.5   25.47
  4635.2   25.34  4790.2   27.33 4886.51   27.46 4954.94    25.4 4974.72   18.94
 5001.49   16.36 5026.45    19.2 5045.06   25.99 5121.09   27.24 5391.04   26.13
 5537.55   27.11 5569.52   25.76 5852.92    26.8 6223.29   25.57 6341.83   26.66
 6819.06   25.41 7167.96   25.74 7578.96   27.52 7982.93   26.28 9265.84   27.47
#Mann= 3 , 0 , 0
 2072.18     .07       0 4886.51    .032       0 5121.09     .07       0
#Block Obstruct= 4 ,-1
 1902.83    4861   27.27    2014  3070.9   26.67 2091.01 3119.45   26.51
  5130.9 9654.52   27.03
Bank Sta=4886.51,5121.09
XS Rating Curve= 0
Exp/Cntr=.3,.1

Type RM Length L Ch R = 1 ,35071.34,50.87,51.84,49.02
XS GIS Cut Line= 4
      3217804.96    13817866.233     3214686.905    13817695.548
     3214584.564    13817699.343     3210412.315    13817479.408
#Sta/Elev= 30
 1831.44   16.67 1842.28   16.47 1862.95   24.38 2656.48    26.3 2686.52   24.13
 2790.77   26.66 4316.91   26.37 4399.08   23.89 4822.78    25.7 4918.78   24.02
  4968.2   14.49  5002.4   18.45 5021.22   24.14 5158.55   25.96 5826.05   25.95
 6005.91   23.08 6043.16   25.39 6288.49   25.18 6351.78   22.85 6376.74   25.53
 7046.09   26.84 7328.13   23.41 7592.82   27.29 7643.57   23.15 7709.75   26.45
 7793.78   23.73 7914.86   26.04 8770.13   25.59 9021.67   29.54 9234.62   27.31
#Mann= 3 , 0 , 0
 1831.44     .07       0 4822.78    .032       0 5158.55     .07       0
#Block Obstruct= 5 ,-1
 1532.42 2617.75   26.16 1546.56 4315.79   26.29 2639.68 4740.89   24.87
 5117.41 9125.51   25.09 5178.14 9161.94   25.88
Bank Sta=4822.78,5158.55
XS Rating Curve= 0
Exp/Cntr=.5,.3

Type RM Length L Ch R = 1 ,35019.49,279.23,120.69,102.85
XS GIS Cut Line= 4
     3217822.474    13817826.826     3214687.251    13817655.507
     3214584.876    13817659.304     3210414.421    13817439.464
#Sta/Elev= 30
    1810    3.84  1869.3   24.36 3900.48   26.49 4184.85    24.3 4325.65   26.22
 4380.15   25.63 4395.17    23.1 4643.46    23.1 4695.62   25.38 4948.78   24.02
  4998.2   14.49  5032.4   18.45 5051.22   24.14 5116.15   25.66 5934.08   25.54
 5994.33   23.74 6272.73   25.38 6347.86   23.23 6362.92   25.59 6799.54   24.15
 7085.35   26.01 7324.22   23.73  7532.4   26.19 7642.05   22.75 7713.95   26.52
 7789.86   23.76  7863.9   26.38 8766.22   25.49 9002.04   28.99 9228.59   28.08
#Mann= 3 , 0 , 0
    1810     .07       0 4948.78    .032       0 5116.15     .07       0
#XS Ineff= 2 , 0
       0 4948.78   24.02 5051.22       0   24.14
Permanent Ineff=
       F       F
#Block Obstruct= 5 ,-1
 1491.47 3017.06   25.64 1517.39 3899.42   26.48 3995.87 4703.17   25.04
 4056.84 4703.17   24.93 5300.73 9306.76   25.99
Bank Sta=4948.78,5116.15
XS Rating Curve= 0
Exp/Cntr=.5,.3

Type RM Length L Ch R = 3 ,34959.15,,,
BEGIN DESCRIPTION:
North "P" Street
END DESCRIPTION:
Bridge Culvert--1,0,-1,-1, 0
Deck Dist Width WeirC Skew NumUp NumDn MinLoCord MaxHiCord MaxSubmerge Is_Ogee
57,32,2.6,0, 10, 10, , , .95, 0, 0,0,,
    3366    4638 4911.69 4947.61 4947.61 5046.93 5046.94 5095.29    5328    6650
   25.99   25.85   24.73   24.73   25.06   25.04   24.73   24.73   25.02   25.06
                                   22.26   22.24
    3366    4638 4911.69 4947.61 4947.61 5046.93 5046.94 5095.29    5328    6650
   25.99   25.85   24.73   24.73   25.06   25.04   24.73   24.73   25.02   25.06
                                   22.26   22.24
Pier Skew, UpSta & Num, DnSta & Num=  ,4980, 4 ,4980, 4 , 3 , 3 , 0 ,,
     1.2     1.2     2.5     2.5
      10   20.23   20.23   22.23
     1.2     1.2     2.5     2.5
      10   20.23   20.23   22.23
Pier Skew, UpSta & Num, DnSta & Num=  ,5011, 4 ,5011, 4 , 3 , 3 , 0 ,,
     1.2     1.2     2.5     2.5
      10   20.23   20.23   22.23
     1.2     1.2     2.5     2.5
      10   20.23   20.23   22.23
BR Coef=-1 , 1 , 0 ,, 0 ,,,.8,0,2,0,
WSPro=,,,, 1 ,,,, 0 ,,,, 0 ,,,,-1 ,-1 ,-1 , 0 , 0 , 0 , 0 , 0
BC Design=,, 0 ,, 0 ,,,,,,
BC HTab HWMax=29.3

Type RM Length L Ch R = 1 ,34898.81,246.68,223.27,191.23
XS GIS Cut Line= 4
     3217483.479    13816376.632     3214632.115    13817552.275
     3214514.975    13817572.728     3211409.244    13817419.776
#Sta/Elev= 30
 1853.16   22.83 1964.59   24.74 2607.43   23.29 2715.01   25.33 2833.06   23.84
 2872.42   21.74 2911.77   24.43 2988.25   25.41 3467.35   25.22 3621.53   26.62
 4830.25    25.4 4948.78   24.02  4998.2   14.49  5032.4   18.45 5051.22    23.5
    5065   24.39 5083.93   23.03 5126.51   24.61 5494.66   24.08 5640.06   25.77
 5759.94   24.35 6236.54   24.87 6266.58   23.65 6496.27   25.45 6690.68   23.89
 7282.02    24.7 7446.59   25.45 7474.84   23.95 7636.96   26.03 8165.79   26.43
#Mann= 4 ,-1 , 0
 1853.16     .07       0 4830.25    .032       0    5065     .07       0
 7282.02     .15       0
#XS Ineff= 4 ,-1
 1853.16 4948.78   24.02 5051.22 5068.26    23.5 5068.26 7953.36   24.46
 7953.36 8165.79    23.5
Permanent Ineff=
       F       F       F       F
#Block Obstruct= 1 ,-1
 1555.18 4058.02   25.99
Bank Sta=4830.25,5065
XS Rating Curve= 0
Exp/Cntr=.5,.3

Type RM Length L Ch R = 1 ,34675.54,719.63,770.83,690.57
XS GIS Cut Line= 4
     3217345.009    13816155.079     3214488.031    13817354.134
     3214392.251    13817401.751     3211372.319     13817382.85
#Sta/Elev= 30
 1849.97    23.5 2669.88   23.47 2805.97   25.42 2896.13   22.08 2944.07   24.16
 3130.69   24.95 3303.93   25.07 3426.42    22.8 3515.59   26.86 3772.84   27.07
 3808.55   25.29 4095.53   26.53 4948.78   24.02  4998.2   14.49  5032.4   18.45
 5051.22   23.82 6003.57   25.46 6096.44   24.77 6133.93   22.57 6165.78   25.16
 6389.83   23.95 6754.55   25.49 6815.06   24.11 7040.01   25.51 7086.46   24.66
 7116.46   20.96 7141.52   23.71 7161.46   25.72 7287.12   24.53 8075.32   25.59
#Mann= 4 ,-1 , 0
 1849.97     .07       0 4948.78    .032       0 5051.22     .07       0
 7141.52     .15       0
#XS Ineff= 1 ,-1
 5304.89 8189.99   24.96
Permanent Ineff=
       F
#Block Obstruct= 4 ,-1
 1682.59 3530.15    26.6 5951.08 7379.98   22.57 7220.6110351.54    25.3
 7998.58 8250.64   26.03
Bank Sta=4948.78,5051.22
XS Rating Curve= 0
Exp/Cntr=.3,.1

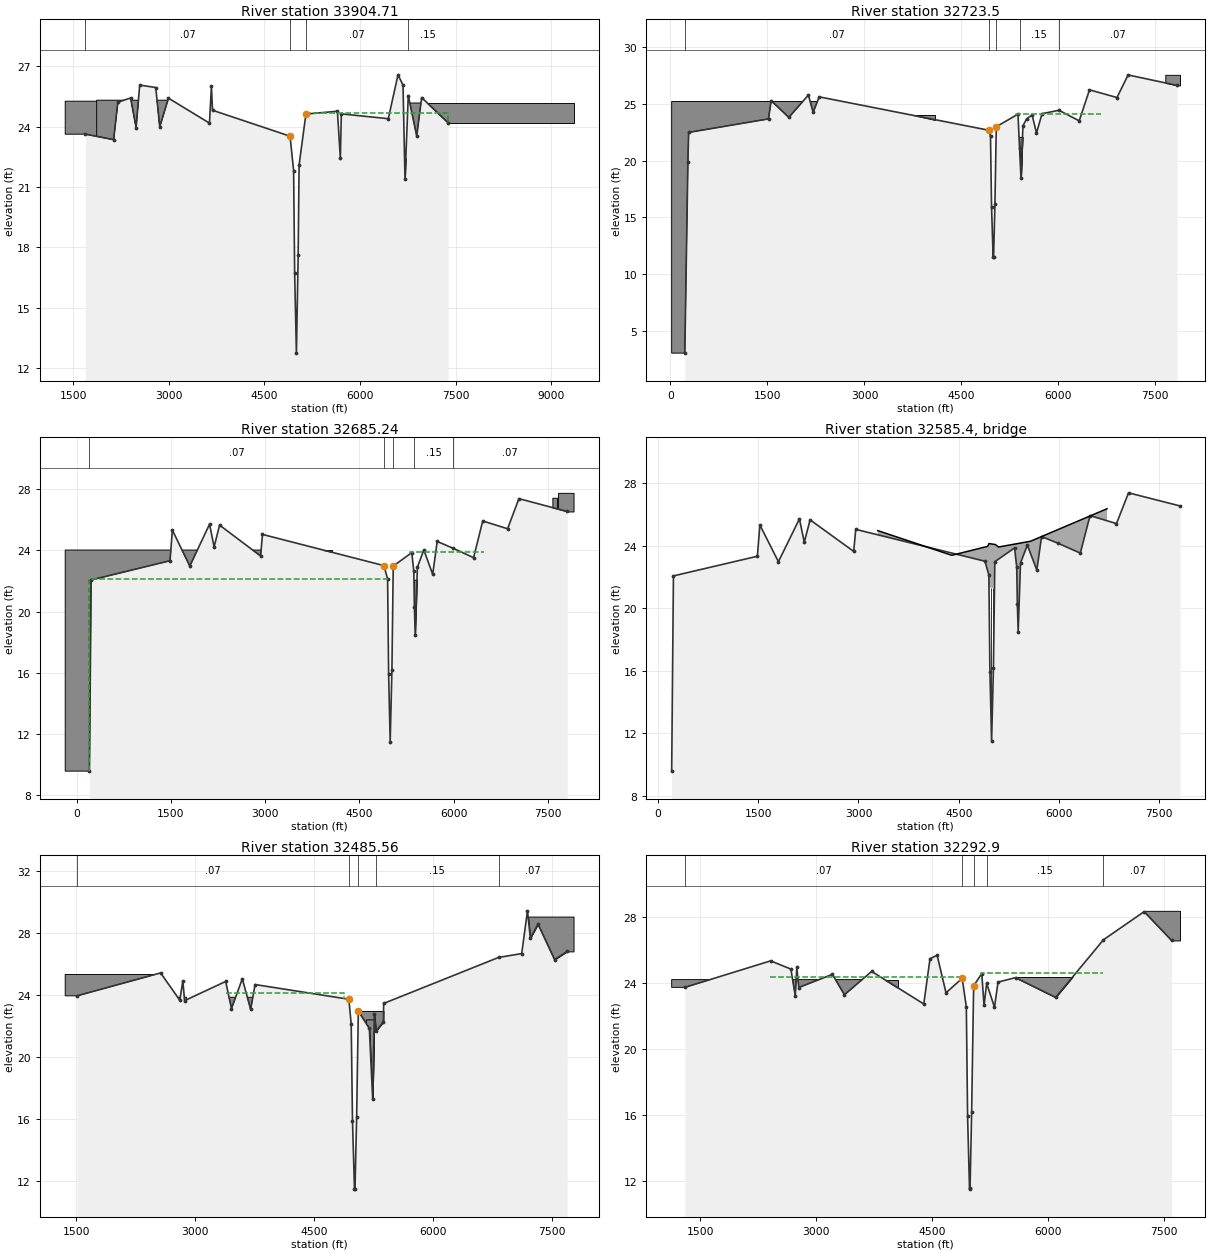
Type RM Length L Ch R = 1 ,33904.71,1081.77,1181.22,1275.56
XS GIS Cut Line= 4
     3217240.325    13816084.552     3214037.076    13816717.193
     3213968.786    13816769.344      3211684.77    13817275.028
#Sta/Elev= 30
 1691.05   23.63 2133.61   23.36 2199.86   25.22 2400.73   25.43 2486.15   23.96
 2543.07   26.07 2794.53   25.95  2857.1      24 2993.88   25.42  3637.1   24.18
 3667.68      26 3684.91   24.82 4901.29   23.53 4957.04   21.82 4973.21   16.74
 5000.76   12.75 5028.49   17.64 5042.96    22.1 5149.73   24.63 5643.96   24.77
 5690.05   22.43 5705.41   24.64 6442.15    24.4 6594.22   26.58  6673.3   26.07
 6704.02   21.39 6755.49   25.55 6888.16   23.54 6965.17   25.45 7381.43    24.2
#Mann= 4 ,-1 , 0
 1691.05     .07       0 4901.29    .032       0 5149.73     .07       0
 6755.49     .15       0
#XS Ineff= 1 ,-1
 5149.03 7530.15   24.66
Permanent Ineff=
       F
#Block Obstruct= 4 ,-1
 1374.29 3054.61   25.27 1868.03 3014.79   25.32 5149.03  7036.4   22.43
 6787.62 9347.68   25.18
Bank Sta=4901.29,5149.73
XS Rating Curve= 0
Exp/Cntr=.3,.1

Type RM Length L Ch R = 1 ,32723.5 ,32.35,38.26,47.62
XS GIS Cut Line= 4
     3218085.183    13816009.755     3213367.868    13815758.843
     3213259.884    13815803.902     3210490.507    13815645.734
#Sta/Elev= 30
  221.66    3.05   269.2   19.89  280.93   22.48 1516.17   23.67 1557.13   25.28
 1830.04    23.8  2133.6   25.77 2206.57   24.25 2300.75   25.61 4924.72   22.67
 4950.28   22.13 4966.44   15.91  4991.3   11.49 4998.08   11.53 5018.85   16.17
 5039.72   22.98 5375.26   24.09 5399.78   21.09 5421.96   18.45 5452.01   23.07
 5508.79   23.66 5593.47   24.03 5661.74   22.42 5747.62   24.13 6008.97   24.43
 6322.47    23.5 6481.63   26.23 6906.44   25.55 7078.76   27.54 7836.54   26.62
#Mann= 5 ,-1 , 0
  221.66     .07       0 4924.72    .032       0 5039.72     .07       0
 5399.78     .15       0 6008.97     .07       0
#XS Ineff= 1 ,-1
 5351.54 6653.01   24.11
Permanent Ineff=
       F
#Block Obstruct= 6 ,-1
    18.2 2339.02    25.2 3681.51 4091.77   23.99 5333.33 5588.17   22.07
 5378.11 6719.45   22.09 7654.15 7881.68   27.55 8129.55 8248.31   22.75
Bank Sta=4924.72,5039.72
XS Rating Curve= 0
Exp/Cntr=.5,.3

Type RM Length L Ch R = 1 ,32685.24,240.27,199.68,181.56
XS GIS Cut Line= 4
     3218080.804    13815970.349     3213337.981    13815732.904
     3213253.941    13815763.497     3210492.788    13815605.799
#Sta/Elev= 30
  205.77    9.57  232.11   22.07 1487.84   23.33 1525.14   25.33 1802.41   22.98
 2116.74   25.72  2189.3   24.23 2276.52   25.66 2928.82   23.64 2958.86   25.05
 4891.72   23.01 4950.28   22.13 4966.44   15.91  4991.3   11.49 5018.85   16.17
 5039.72   22.98 5334.93   23.86 5367.28   22.63 5376.39    20.3 5389.14    18.5
 5424.04    22.9 5526.72   24.04 5667.77   22.44 5739.41   24.59  5984.7   24.16
 6318.49   23.53 6464.06   25.93  6859.6   25.42 7039.83   27.39 7809.62   26.55
#Mann= 5 ,-1 , 0
  205.77     .07       0 4891.72    .032       0 5039.72     .07       0
 5376.39     .15       0  5984.7     .07       0
#XS Ineff= 4 ,-1
  205.77 4950.28   22.13 5039.72 5306.03   22.98 5306.03 6489.19   23.93
 6489.19 7809.62   22.98
Permanent Ineff=
       F       F       F       F
#Block Obstruct= 4 ,-1
 -180.31 4058.32   24.03 5251.42 5515.36   22.09 7572.24 7645.05   27.45
 7663.25 7908.99   27.77
Bank Sta=4891.72,5039.72
XS Rating Curve= 0
Exp/Cntr=.5,.3

Type RM Length L Ch R = 3 ,32585.4 ,,,
BEGIN DESCRIPTION:
North "L" Street
END DESCRIPTION:
Bridge Culvert--1,0,-1,-1, 0
Deck Dist Width WeirC Skew NumUp NumDn MinLoCord MaxHiCord MaxSubmerge Is_Ogee
103,39,2.6,0, 8, 8, , , .95, 0, 0,0,,
    3289    4396 4931.88 4952.62 5047.25  5095.2    5574    6718
   24.97   23.39   23.96   24.14   24.08   23.92   24.29   26.37
                           21.34   21.28
    3289    4396 4931.88 4952.62 5047.25  5095.2    5574    6718
   24.97   23.39   23.96   24.14   24.08   23.92   24.29   26.37
                           21.34   21.28
Pier Skew, UpSta & Num, DnSta & Num=  ,4983, 4 ,4983, 4 , 3 , 3 , 0 ,,
     1.2     1.2     2.5     2.5
      10   19.29   19.29   21.29
     1.2     1.2     2.5     2.5
      10   19.29   19.29   21.29
Pier Skew, UpSta & Num, DnSta & Num=  ,5016, 4 ,5016, 4 , 3 , 3 , 0 ,,
     1.2     1.2     2.5     2.5
      10   19.29   19.29   21.29
     1.2     1.2     2.5     2.5
      10   19.29   19.29   21.29
BR Coef=-1 , 1 , 0 ,, 0 ,,,.8,0,2,0,
WSPro=,,,, 1 ,,,, 0 ,,,, 0 ,,,,-1 ,-1 ,-1 , 0 , 0 , 0 , 0 , 0
BC Design=,, 0 ,, 0 ,,,,,,
BC HTab HWMax=27.85

Type RM Length L Ch R = 1 ,32485.56,169.05,192.66,192.52
XS GIS Cut Line= 4
     3216680.807    13815553.267     3213252.604    13815556.516
     3213118.838    13815605.799     3210513.909     13815429.79
#Sta/Elev= 30
 1507.38   23.97 2561.14   25.45  2803.5   23.69 2842.03   24.94 2863.91   23.66
 3382.03    24.9 3455.36   23.15 3592.03   25.07 3697.03    23.1 3753.03    24.7
 4935.59   23.75 4965.28   22.13 4981.44   15.91  5006.3   11.49 5013.08   11.53
 5033.85   16.17 5054.72   22.98 5193.93   21.87 5236.17   17.28 5257.99   22.81
 5278.17   21.69 5371.49    22.3 5374.34   23.48 6823.58   26.45 7115.46    26.7
  7188.3   29.46 7224.47   27.69 7320.67    28.6 7529.81   26.31 7689.01   26.84
#Mann= 5 ,-1 , 0
 1507.38     .07       0 4935.59    .032       0 5054.72     .07       0
 5278.17     .15       0 6823.58     .07       0
#XS Ineff= 4 ,-1
 1507.38 3389.08   22.13 3389.08 4878.27   24.14 4878.27 4965.28   22.13
 5054.72 7689.01   22.98
Permanent Ineff=
       F       F       F       F
#Block Obstruct= 6 ,-1
 1358.36 2576.79   25.35 2763.08 2889.48   23.88 3373.15  4193.4   23.88
 5081.93 5726.65   22.99 5151.45 5259.97   22.45 7187.71 7769.06   29.09
Bank Sta=4935.59,5054.72
XS Rating Curve= 0
Exp/Cntr=.5,.3

Type RM Length L Ch R = 1 ,32292.9 ,492.1,499.43,512.69
XS GIS Cut Line= 4
     3216805.321    13815522.138     3213214.485     13815405.64
     3213013.258     13815405.64     3210501.775    13815413.188
#Sta/Elev= 30
 1298.71   23.75 2409.43   25.36 2672.02   24.86 2728.63   23.24 2748.63   24.96
 2773.65   23.74 3209.53   24.54 3365.62    23.3 3718.41   24.72 4393.77   22.74
  4474.3   25.49 4566.84    25.7  4681.6   23.42 4891.44    24.3    4945   22.56
 4961.44   15.91  4986.3   11.49 4993.08   11.53 5013.85   16.17 5039.76   23.84
 5144.76   24.59 5174.76   22.65 5208.09      24 5309.76   22.54 5355.58   24.07
 5582.58   24.34 6102.38   23.14 6721.39   26.64 7248.55   28.35 7604.16    26.6
#Mann= 5 ,-1 , 0
 1298.71     .07       0 4891.44    .032       0 5039.76     .07       0
 5208.09     .15       0 6721.39     .07       0
#XS Ineff= 2 ,-1
 5133.11 6717.86    24.6 2401.59 4878.27   24.35
Permanent Ineff=
       F       F
#Block Obstruct= 3 ,-1
 1127.42 4065.98   24.22 5588.62 7279.53   24.38 7259.39 7713.31    28.4
Bank Sta=4891.44,5039.76
XS Rating Curve= 0
Exp/Cntr=.3,.1

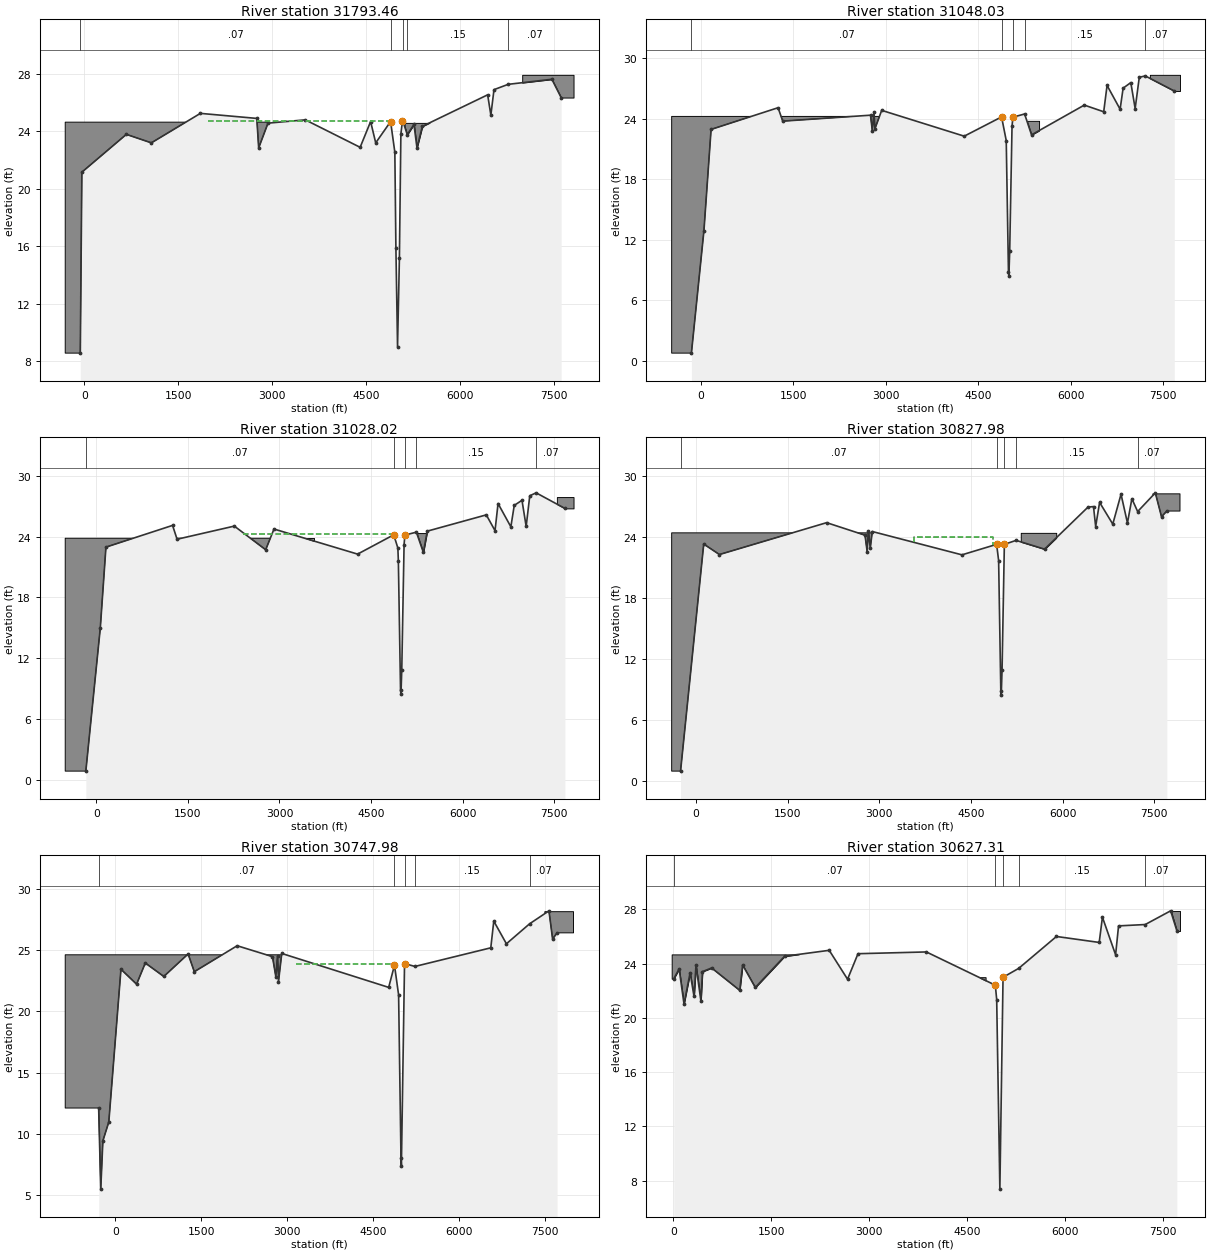
Type RM Length L Ch R = 1 ,31793.46,739.97,745.44,747.89
XS GIS Cut Line= 4
     3218185.888    13815252.277     3213179.522    13814908.388
     3213090.031    13814904.376     3210527.286    13814797.942
#Sta/Elev= 30
  -63.99    8.56  -39.13   21.14  670.95   23.77 1069.81   23.18 1852.28   25.23
 2752.37   24.88 2782.44   22.83 2931.18   24.55 3526.77   24.78 4401.41   22.87
 4568.68   24.66    4650   23.18 4887.39   24.66 4955.21   22.53 4972.02    15.9
 4998.29    9.02 5027.88   15.14 5051.55    23.8 5076.73   24.72 5078.41   24.77
 5153.46   23.75 5260.38   24.46 5308.27   22.83 5394.48   24.33 6436.19   26.52
 6487.36   25.11 6537.35   26.88 6764.72   27.25 7461.03    27.6 7608.72   26.33
#Mann= 5 ,-1 , 0
  -63.99     .07       0 4887.39    .032       0 5078.41     .07       0
 5153.46     .15       0 6764.72     .07       0
#XS Ineff= 1 ,-1
 1970.42 4882.82   24.73
Permanent Ineff=
       F
#Block Obstruct= 3 ,-1
 -304.89 2937.43   24.62 5110.35 5758.82   24.57 6987.49  7806.6   27.91
Bank Sta=4887.39,5076.73
XS Rating Curve= 0
Exp/Cntr=.3,.1

Type RM Length L Ch R = 1 ,31048.03,20.32,20.01,20.12
XS GIS Cut Line= 4
     3218361.027    13814540.335     3213262.515     13814172.94
     3213170.438    13814157.587     3210541.612    13814091.184
#Sta/Elev= 30
 -155.26     .78    48.1   12.93  163.96   22.95 1250.79    25.1 1326.89   23.77
 2750.86   24.36 2781.23   22.76 2807.27   24.68 2822.31   23.01 2932.05   24.84
 4271.18   22.28 4877.47   24.19 4952.99   21.85 4988.92    8.83 4995.78    8.46
 5009.14   10.86 5046.91   23.24 5060.62   24.16 5250.71   24.48 5363.42   22.41
 6219.47   25.36 6534.57    24.7 6589.23   27.31 6800.73   24.95 6849.67   27.04
 6974.33   27.59 7044.74   25.02  7111.9   28.12  7209.4   28.25 7679.48   26.76
#Mann= 5 ,-1 , 0
 -155.26     .07       0 4877.47    .032       0 5060.62     .07       0
 5250.71     .15       0  7209.4     .07       0
#XS Ineff= 1 ,-1
 2630.26 4871.44   24.11
Permanent Ineff=
       F
#Block Obstruct= 3 ,-1
 -475.54 2937.43   24.24 5246.87 5485.78    23.8 7283.28 7772.47   28.36
Bank Sta=4877.47,5060.62
XS Rating Curve= 0
Exp/Cntr=.3,.1

Type RM Length L Ch R = 1 ,31028.02,200.62,200.04,201.6
XS GIS Cut Line= 4
     3218375.038    13814515.816     3213264.879    13814153.058
     3213172.344    13814137.629     3210542.117    13814071.191
#Sta/Elev= 30
 -171.77     .83   65.52      15   157.7   22.98 1249.32   25.13 1322.92   23.76
 2261.04   25.06 2774.85   22.72 2910.53   24.77 4280.32   22.29 4872.63    24.2
 4939.95   22.89 4948.09   21.65 4983.92    8.83 4990.78    8.46 5004.14   10.86
 5041.91   23.24 5055.29   24.17 5243.29   24.46 5357.73   22.46 5421.38   24.56
 6388.84   26.17 6531.73   24.61 6581.42   27.29 6791.28   24.99 6846.83   27.11
  6973.5   27.61 7041.89   25.03 7101.14   28.06 7205.26   28.35 7676.14   26.81
#Mann= 5 ,-1 , 0
 -171.77     .07       0 4872.63    .032       0 5055.29     .07       0
 5243.29     .15       0 7205.26     .07       0
#XS Ineff= 1 ,-1
 2402.73 4860.07   24.24
Permanent Ineff=
       F
#Block Obstruct= 3 ,-1
 -509.67 3563.14   23.86 5258.25  5474.4   24.37 7544.94 7817.98   27.93
Bank Sta=4872.63,5055.29
XS Rating Curve= 0
Exp/Cntr=.3,.1

Type RM Length L Ch R = 1 ,30827.98,80.4,80,80.83
XS GIS Cut Line= 4
     3218487.128    13814326.665      3213288.52    13813954.239
     3213191.409    13813938.047     3210547.168    13813871.254
#Sta/Elev= 30
 -250.61     .97  128.54   23.27   385.3   22.24 2139.26   25.37 2767.05   24.14
 2802.61   22.53 2823.22   24.56  2853.3   22.88 2886.21    24.5 4352.99   22.21
 4920.44   23.24 4953.09   21.65 4988.92    8.83 4995.78    8.46 5009.14   10.86
 5046.91   23.24 5238.66   23.63 5704.72   22.77 6415.46    26.9 6505.21   26.95
 6540.58   24.99 6604.96   27.36 6820.59   25.23 6955.63   28.16 7060.66   25.34
 7133.11   27.72 7227.53   26.46 7516.91    28.3 7618.07   25.95 7704.86   26.51
#Mann= 5 ,-1 , 0
 -250.61     .07       0 4920.44    .032       0 5046.91     .07       0
 5238.66     .15       0 7227.53     .07       0
#XS Ineff= 1 ,-1
 3563.14 4860.07   23.99
Permanent Ineff=
       F
#Block Obstruct= 3 ,-1
  -395.9 2926.05   24.37 5315.13 5895.34   24.37 7476.68 7920.36    28.2
Bank Sta=4920.44,5046.91
XS Rating Curve= 0
Exp/Cntr=.3,.1

Type RM Length L Ch R = 1 ,30747.98,121.96,120.67,119.19
XS GIS Cut Line= 4
     3218536.167    13814249.604     3213297.976    13813874.711
     3213199.035    13813858.214     3210549.188     13813791.28
#Sta/Elev= 30
 -289.72   12.11 -253.16    5.49 -216.25    9.43  -112.6   10.97   99.61   23.44
  372.48   22.22  524.49   23.95  847.59   22.85 1271.88   24.69 1379.97   23.24
 2128.04   25.36 2744.47   24.47 2803.19   22.84 2833.27   24.51 2849.65   22.44
 2906.42   24.73 4773.22   21.96 4874.29   23.77 4946.32   21.35 4988.02    8.04
 4994.95    7.38    5050    23.9 5232.08   23.67 6555.47   25.19 6607.74   27.37
 6828.32   25.52 7232.73   27.15 7570.99   28.21 7634.79   25.91 7712.88   26.41
#Mann= 5 ,-1 , 0
 -289.72     .07       0 4874.29    .032       0    5050     .07       0
 5232.08     .15       0 7232.73     .07       0
#XS Ineff= 1 ,-1
 3161.47 4860.02   23.89
Permanent Ineff=
       F
#Block Obstruct= 2 ,-1
 -873.72 2948.81   24.62 7499.43    8000   28.14
Bank Sta=4874.29,5050
XS Rating Curve= 0
Exp/Cntr=.3,.1

Type RM Length L Ch R = 1 ,30627.31,1036.43,1037.3,1037.12
XS GIS Cut Line= 4
 3218265.447402113814068.7240062     3213330.308    13813757.546
     3213234.198    13813742.058     3210568.619    13813664.363
#Sta/Elev= 30
    5.38   22.89   87.15   23.61  161.64   21.03  255.18   23.32  315.29   21.58
  345.35   23.87   420.5   21.26  444.62   23.41  585.83   23.68 1015.62   22.03
 1059.97    23.9 1253.98   22.24 1702.92   24.54 2386.93   24.98 2667.97   22.85
 2828.24   24.73    3876   24.86 4932.42 22.40894953.463  21.3535002.092  7.3796
 5050.81 22.9917 5290.82   23.65 5869.18      26  6524.4   25.56 6573.93   27.42
 6775.67   24.65 6820.99   26.78 7229.68   26.88 7619.14   27.89 7714.39   26.42
#Mann= 5 ,-1 , 0
    5.38     .07       0 4932.42    .032       0 5050.81     .15       0
 5290.82     .15       0 7229.68     .07       0
#Block Obstruct= 3 ,-1
   -27.3 2102.39   24.68 4695.16 4783.31      23 7613.31 7762.59   27.88
Bank Sta=4932.42,5050.81
XS Rating Curve= 0
Exp/Cntr=.3,.1