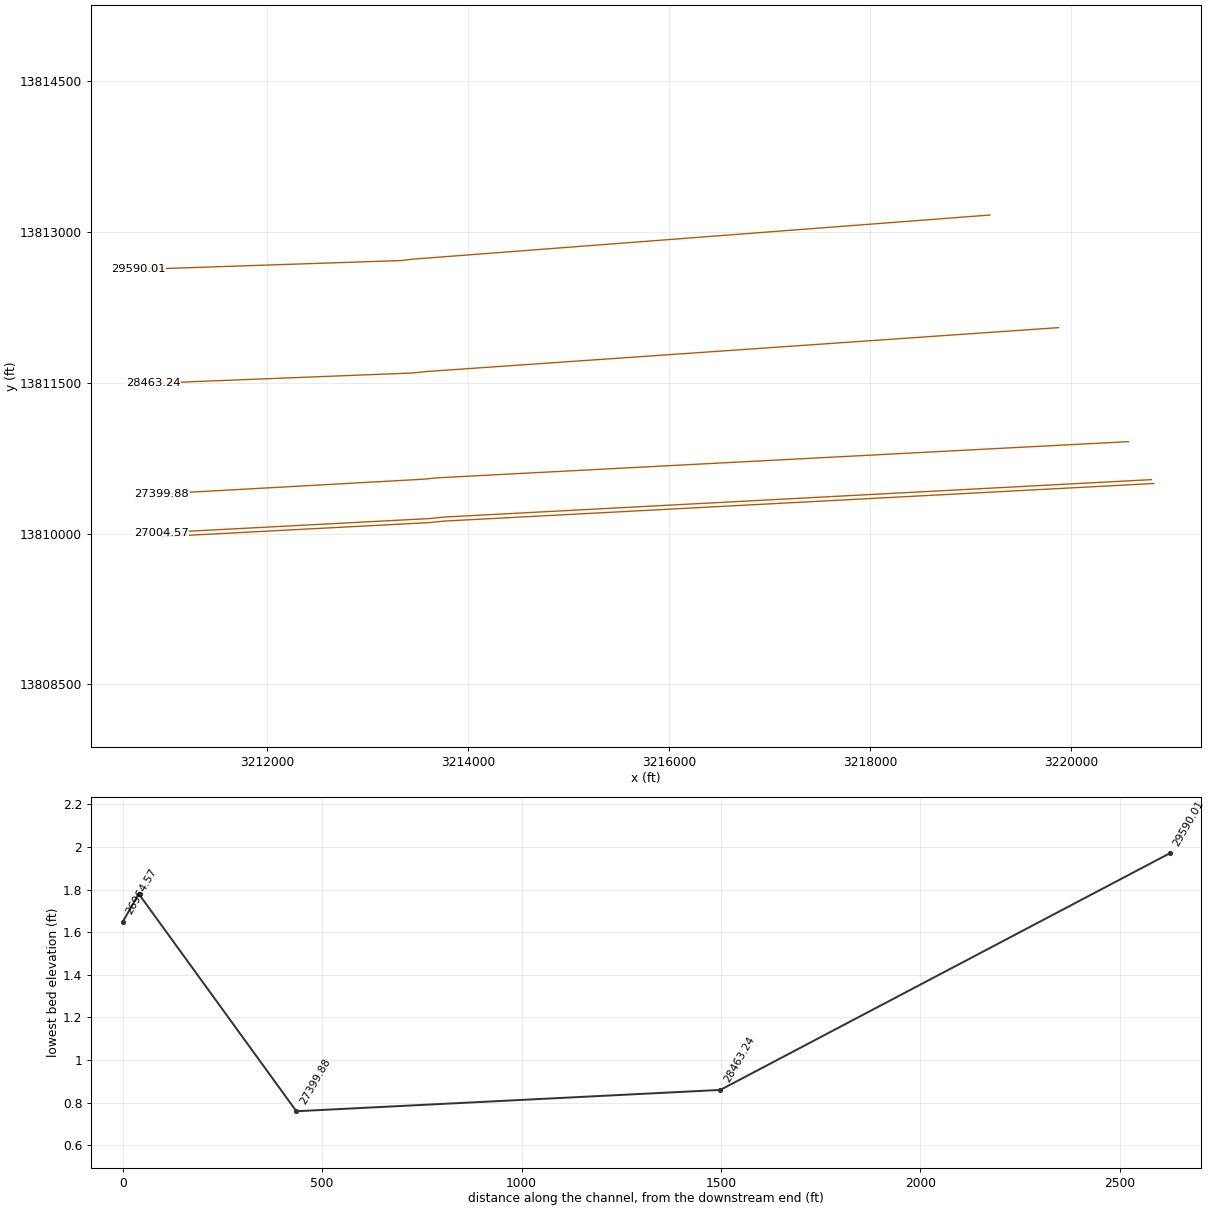
HEC-RAS study B106_00_00.prj: B106-00-00

--- B106_00_00.g03 (geometry) --- (continued)

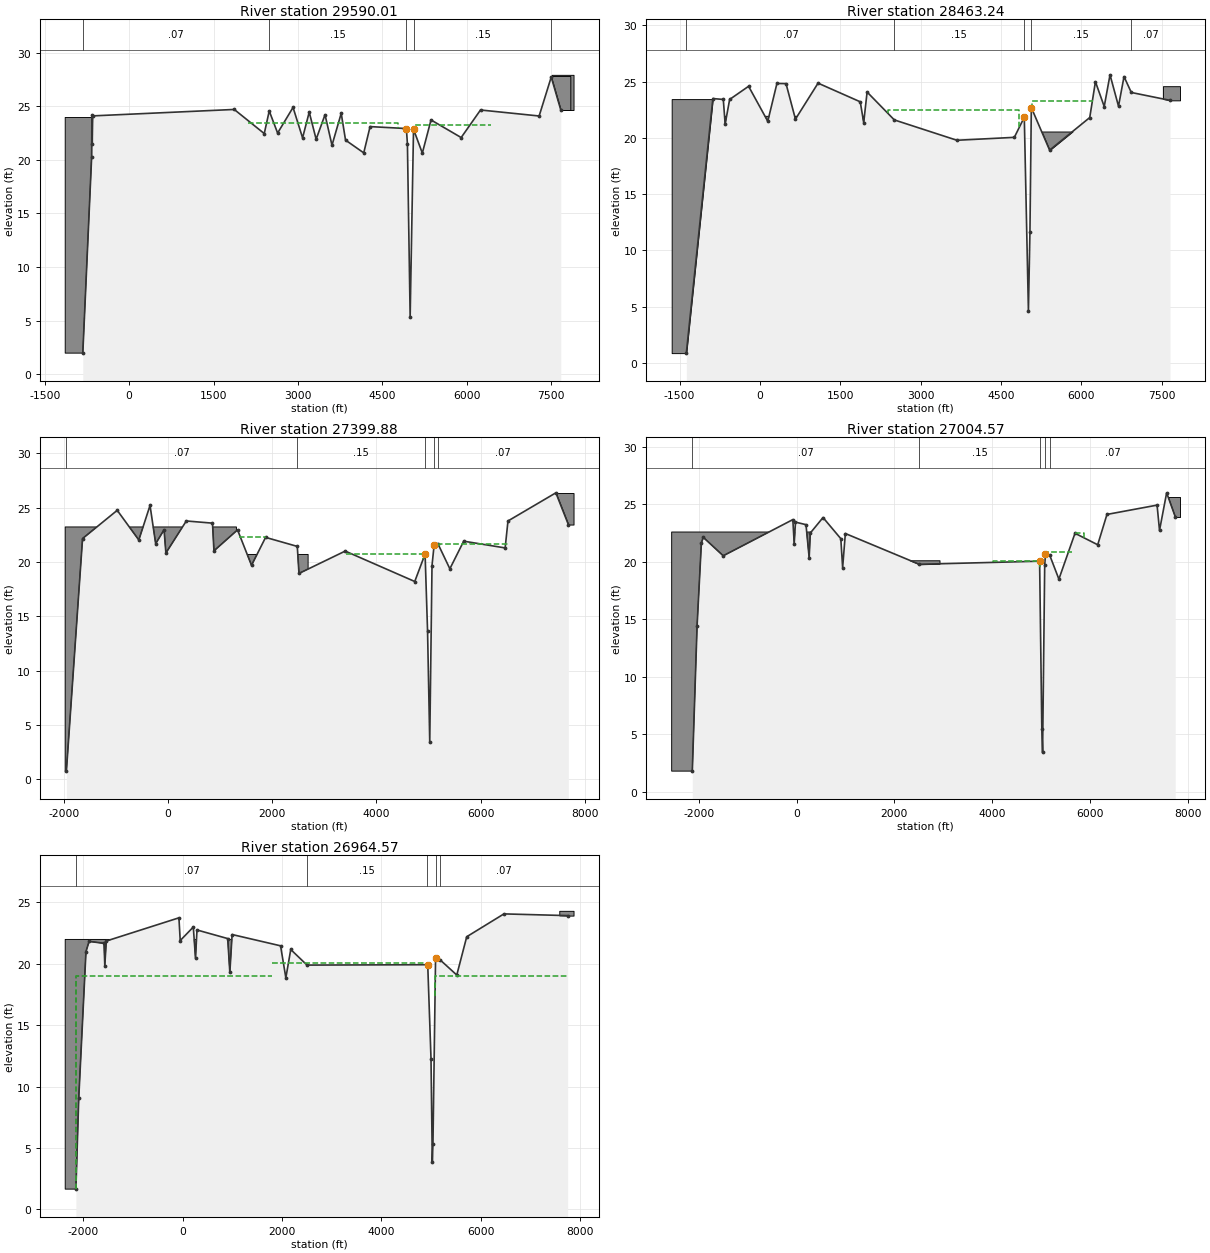
Type RM Length L Ch R = 1 ,29590.01,1128.02,1126.77,1126.6
XS GIS Cut Line= 4
     3219191.188    13813170.745      3213439.08    13812730.906
     3213331.464    13812717.618     3210716.441    13812629.606
#Sta/Elev= 30
 -822.53    1.97 -665.57   20.28 -661.29   24.14 -655.29   21.48 -647.32    24.1
 1868.48    24.7  2401.9   22.45 2490.08   24.56 2639.24    22.5 2913.39   24.89
 3082.69   22.05 3200.76   24.45 3323.85   21.92  3481.6   24.21  3605.4   21.36
 3769.34   24.34  3846.1   21.84 4169.54   20.65 4282.37    23.1 4927.25   22.92
 4945.78   21.48 4994.24    5.35 5054.22   22.85 5210.76   20.63  5365.3   23.72
 5900.85   22.08 6244.55   24.65 7286.38   24.09 7501.44   27.72 7671.32   24.65
#Mann= 5 ,-1 , 0
 -822.53     .07       0 2490.08     .15       0 4927.25    .032       0
 5054.22     .15       0 7501.44     .07       0
#XS Ineff= 2 ,-1
 2106.94 4780.43   23.42 5076.22 6430.03   23.29
Permanent Ineff=
       F       F
#Block Obstruct= 4 ,-1
-1135.38 -612.06   23.95 7488.05 7624.57   27.22 7510.81 7897.61   27.93
 7510.81 7840.73   27.82
Bank Sta=4927.25,5054.22
XS Rating Curve= 0
Exp/Cntr=.3,.1

Type RM Length L Ch R = 1 ,28463.24,1067.42,1063.36,1066.4
XS GIS Cut Line= 4
     3219874.232    13812049.853      3213582.56    13811612.805
     3213452.226    13811598.675     3210864.264    13811496.301
#Sta/Elev= 30
-1373.71     .86  -878.3    23.5 -683.79   23.42 -648.95   21.23 -565.46   23.42
 -211.81   24.59  146.47   21.48  317.18   24.84  486.85   24.83  662.97   21.67
 1085.08   24.87 1872.56   23.21 1936.94   21.36 2000.23   24.08  2508.3    21.6
 3676.52   19.79 4748.54   20.05 4934.45   21.84 5011.32    4.63 5040.02   11.66
 5065.55    22.7 5407.17   18.91 6156.15   21.81 6262.12      25 6426.36   22.79
 6534.58   25.61 6692.95   22.82  6795.7   25.45 6931.98   24.04 7654.22   23.34
#Mann= 5 ,-1 , 0
-1373.71     .07       0  2508.3     .15       0 4934.45    .032       0
 5065.55     .15       0 6931.98     .07       0
#XS Ineff= 2 ,-1
 5076.22  6219.9   23.27  2384.6 4842.17   22.45
Permanent Ineff=
       F       F
#Block Obstruct= 5 ,-1
-1647.33 -828.21   23.45 -731.44 2116.06   21.92 2607.51 3005.69   20.57
 5125.48 6151.19   20.57 7522.18 7840.73    24.6
Bank Sta=4934.45,5065.55
XS Rating Curve= 0
Exp/Cntr=.3,.1

Type RM Length L Ch R = 1 ,27399.88,394.21,395.31,394.23
XS GIS Cut Line= 4
     3220571.287     13810914.95     3213692.782    13810554.965
     3213560.986    13810541.417     3210946.387    13810395.845
#Sta/Elev= 30
-1954.58     .76-1644.21   22.16 -978.51   24.76 -563.74   22.03 -348.45   25.21
 -239.99   21.69  -78.78   22.97  -43.89   20.83  348.15   23.78  851.09   23.58
  879.04   21.03 1332.01   22.96 1600.41    19.7 1870.91   22.27 2479.39   21.44
 2511.65   18.95  3399.5   21.01 4734.76   18.21 4933.34   20.74 4980.61   13.68
 5022.91    3.41 5066.25   19.68 5107.56    21.6 5178.32    21.7 5408.94   19.38
  5674.8   21.92 6470.79    21.3 6524.99   23.78 7444.36   26.37 7684.48   23.45
#Mann= 5 ,-1 , 0
-1954.58     .07       0 2479.39     .15       0 4933.34    .032       0
 5107.56     .15       0 5178.32     .07       0
#XS Ineff= 3 ,-1
 1367.46 1868.03   22.28 5202.78 6551.84    21.7 3415.24  4894.2   20.76
Permanent Ineff=
       F       F       F
#Block Obstruct= 3 ,-1
-1977.25 1310.58   23.23 1344.71 2687.14    20.7  7465.3 7783.85   26.35
Bank Sta=4933.34,5107.56
XS Rating Curve= 0
Exp/Cntr=.3,.1

Type RM Length L Ch R = 1 ,27004.57,40.05,40,40.06
XS GIS Cut Line= 4
     3220798.968    13810536.648     3213753.178    13810163.788
     3213608.751    13810148.944     3210944.285    13810008.747
#Sta/Elev= 30
-2130.34    1.78-2032.79   14.42-1945.05   21.63-1907.03   22.13-1498.54   20.52
  -76.15   23.67  -47.96   21.59  -21.92   23.45   192.9   23.23  257.87   20.36
  280.84    22.5  541.04   23.85  904.49   22.01  941.76   19.49  997.15   22.46
 2508.08   19.78    4967   20.05 5012.47    5.43 5027.91    3.41 5071.25   19.68
 5086.39   20.64 5172.71   20.58 5361.19   18.49 5690.46   22.48 6154.59   21.48
 6343.48   24.12 7367.69   24.93 7417.64   22.73 7563.15      26 7738.65   23.93
#Mann= 5 ,-1 , 0
-2130.34     .07       0 2508.08     .15       0    4967    .032       0
 5086.39     .15       0 5172.71     .07       0
#XS Ineff= 4 ,-1
 5707.84 5872.78   22.53   709.9 1064.85    21.9 5098.39 5629.56   20.82
 4011.55 4969.16   20.04
Permanent Ineff=
       F       F       F       F
#Block Obstruct= 3 ,-1
-2552.09   756.1   22.59  1815.7  2921.5   20.13 7549.49 7836.18   25.64
Bank Sta=4967,5086.39
XS Rating Curve= 0
Exp/Cntr=.5,.3

Type RM Length L Ch R = 1 ,26964.57,214.49,202.15,199.13
XS GIS Cut Line= 4
     3220823.487    13810498.118      3213756.28    13810123.896
     3213611.849    13810109.052     3210946.387    13809968.802
#Sta/Elev= 30
-2146.57    1.65-2089.46    9.05-1943.91      21-1880.84   21.83-1580.34   21.67
-1565.32   19.85-1535.73   21.86   -74.3   23.75  -48.19    21.9  215.02      23
  259.13   20.47  289.17   22.76  907.16   22.06  950.09    19.3  995.61   22.39
 1970.34   21.47 2076.67   18.86 2175.14   21.17 2502.41    19.9 4925.81   19.93
 4930.54   19.93 4996.48   12.28 5022.45    3.85 5035.67    5.33 5088.29   20.44
  5173.1   20.35 5514.94   19.09 5715.18   22.21 6463.34   24.07 7744.88   23.93
#Mann= 5 ,-1 , 0
-2146.57     .07       0 2502.41     .15       0 4925.81    .032       0
 5088.29     .15       0  5173.1     .07       0
#XS Ineff= 4 ,-1
-2146.57 1802.05   19.03 1802.05 4860.07   20.04 4860.07  4932.4   19.03
  5077.6 7744.88   19.03
Permanent Ineff=
       F       F       F       F
#Block Obstruct= 2 ,-1
-2361.77 1160.41   21.99 7576.79 7863.48   24.32
Bank Sta=4930.54,5088.29
XS Rating Curve= 0
Exp/Cntr=.5,.3