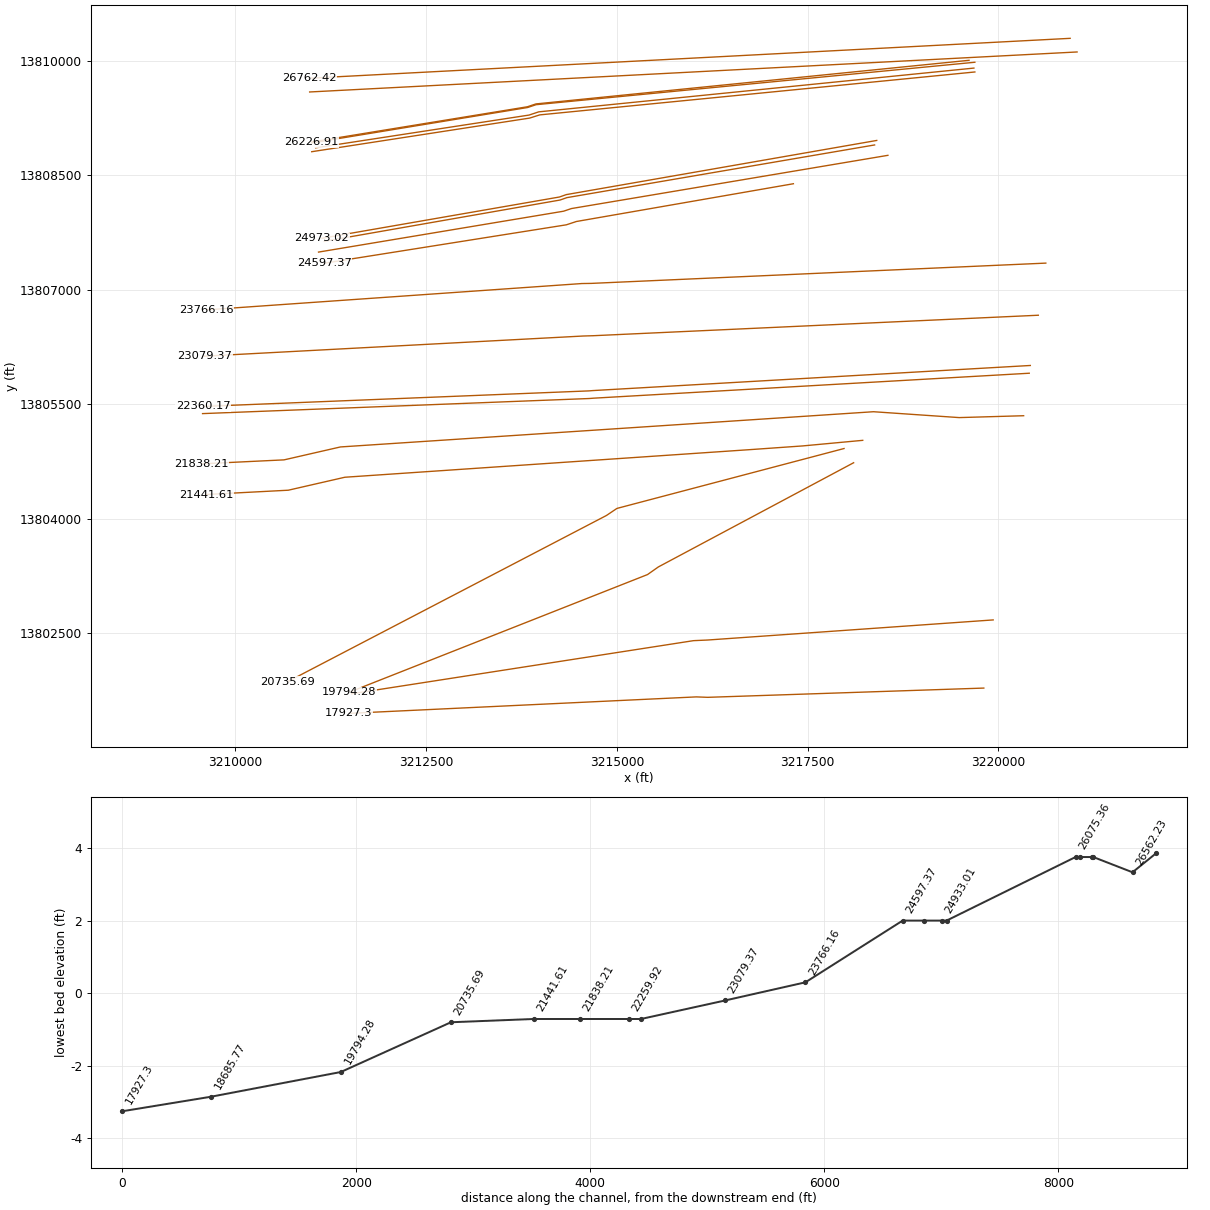
HEC-RAS study B106_00_00.prj: B106-00-00

--- B106_00_00.g03 (geometry) --- (continued)

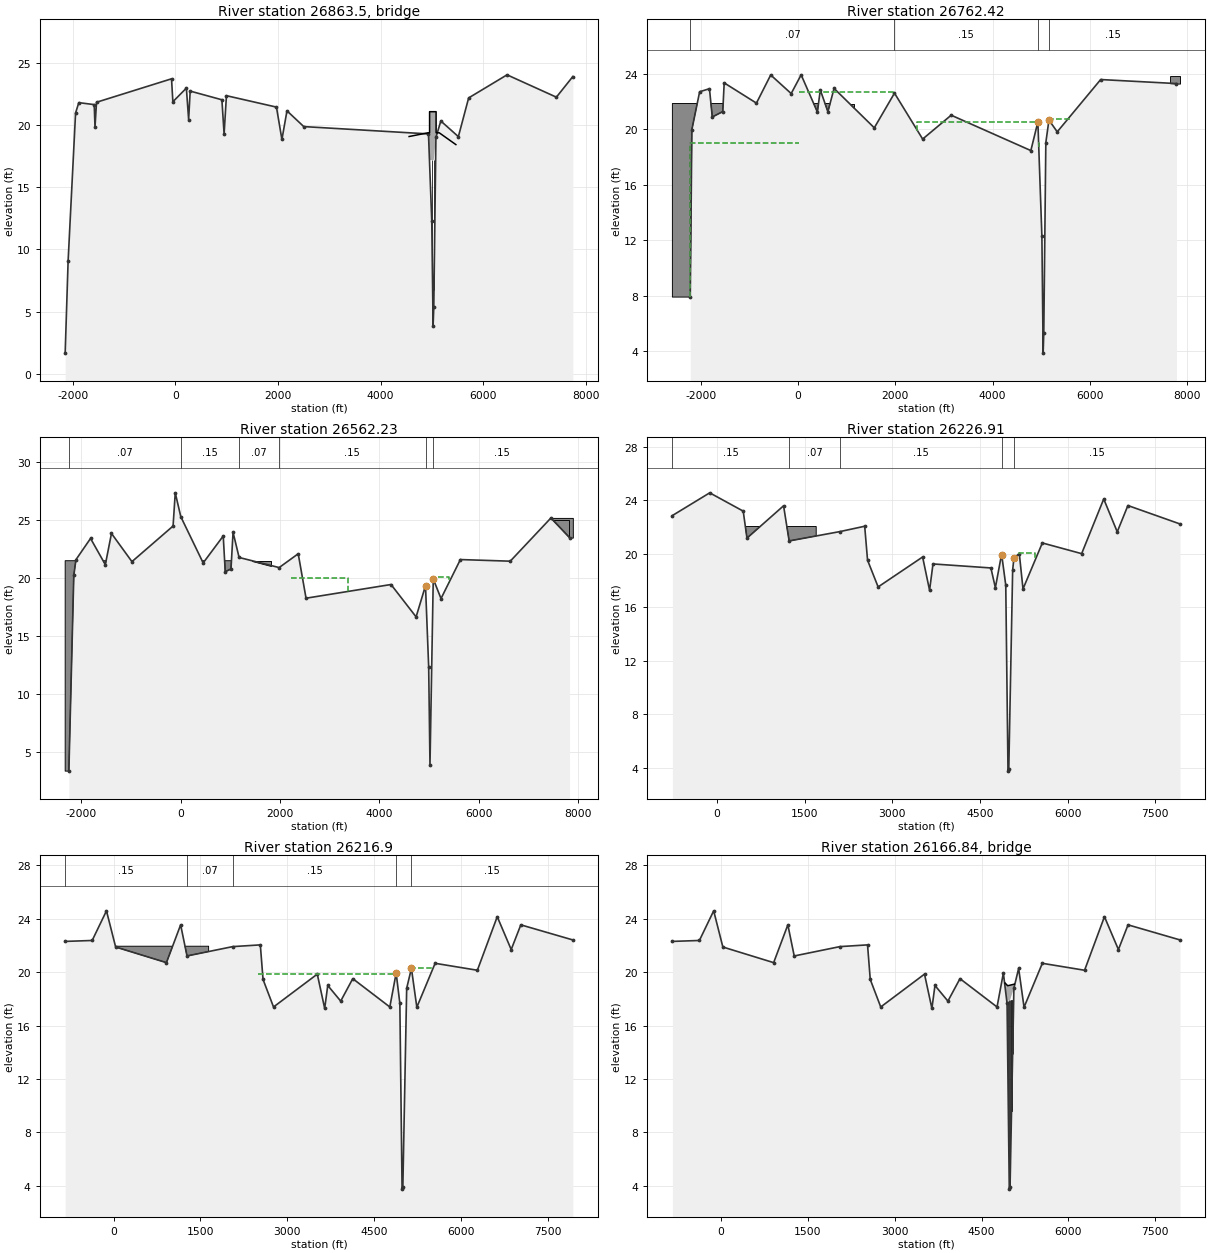
Type RM Length L Ch R = 3 ,26863.5 ,,,
BEGIN DESCRIPTION:
Spencer Highway
END DESCRIPTION:
Bridge Culvert--1,0,-1,-1, 0
Deck Dist Width WeirC Skew NumUp NumDn MinLoCord MaxHiCord MaxSubmerge Is_Ogee
46,98,2.6,0, 8, 8, , , .95, 0, 0,0,,
    4555    4923 4953.99    4954    5081 5081.01    5142    5466
    19.1    19.4    19.4    21.1    21.1    19.4    19.4   18.45
                       0    17.2    17.2       0
    4565    4933 4963.99    4964    5091 5091.01    5152    5476
    19.1    19.4    19.4    21.1    21.1    19.4    19.4   18.45
                       0    17.2    17.2       0
Pier Skew, UpSta & Num, DnSta & Num=  ,5008, 4 ,5028, 4 , 3 , 3 , 0 ,,
     1.4     1.4     2.5     2.5
       0   16.81   16.81   19.31
     1.4     1.4     2.5     2.5
       0   16.81   16.81   19.31
Pier Skew, UpSta & Num, DnSta & Num=  ,5040, 4 ,5060, 4 , 3 , 3 , 0 ,,
     1.4     1.4     2.5     2.5
       0   16.81   16.81   19.31
     1.4     1.4     2.5     2.5
       0   16.81   16.81   19.31
BR Coef=-1 , 1 , 0 ,, 0 ,,,.8,0,2,0,
WSPro=,,,, 1 ,,,, 0 ,,,, 0 ,,,,-1 ,-1 ,-1 , 0 , 0 , 0 , 0 , 0
BR U #Sta/Elev= 30
-2146.57    1.65-2089.46    9.05-1943.91      21-1880.84   21.83-1580.34   21.67
-1565.32   19.85-1535.73   21.86   -74.3   23.75  -48.19    21.9  215.02      23
  259.13   20.47  289.17   22.76  907.16   22.06  950.09    19.3  995.61   22.39
 1970.34   21.47 2076.67   18.86 2175.14   21.17 2502.41    19.9  4932.4   19.31
 4996.48   12.28 5022.45    3.85 5035.67    5.33  5077.6   19.03  5173.1   20.35
 5514.94   19.09 5715.18   22.21 6463.34   24.07 7424.66   22.27 7744.88   23.93
BR U #Mann= 5
-2146.57     .07 2502.41     .15  4932.4    .015  5077.6     .15  5173.1     .07
BR D #Sta/Elev= 30
-2212.76    7.89-2180.08   19.96-2020.22   22.69-1818.67   22.91-1760.32   20.87
-1545.16   21.26-1515.77   23.33 -853.34   21.87  -560.1    23.9 -139.52   22.56
   65.11   23.91  399.03   21.23  458.83   22.82     615   21.25  741.84   22.93
 1568.07   20.09 1983.03   22.59 2561.71   19.28 3145.99      21 3286.83   19.59
 4928.55   20.51  4947.4   19.31 5011.48   12.28 5037.45    3.85 5050.67    5.33
  5092.6   19.03 5156.57   20.65 5326.69    19.8 6219.39   23.57 7777.22   23.28
BR D #Mann= 4
-2212.76     .07 1983.03     .15  4947.4    .015  5092.6     .15
BC Design=,, 0 ,, 0 ,,,,,,
BC HTab HWMax=24.88

Type RM Length L Ch R = 1 ,26762.42,194.27,200.19,192.65
XS GIS Cut Line= 2
     3220939.079    13810294.956     3210962.812    13809771.706
#Sta/Elev= 30
-2212.76    7.89-2180.08   19.96-2020.22   22.69-1818.67   22.91-1760.32   20.87
-1545.16   21.26-1515.77   23.33 -853.34   21.87  -560.1    23.9 -139.52   22.56
   65.11   23.91  399.03   21.23  458.83   22.82     615   21.25  741.84   22.93
 1568.07   20.09 1983.03   22.59 2561.71   19.28 3147.76      21 4784.77   18.45
 4928.55   20.51 4930.07   20.42 5011.48   12.28 5037.45    3.85 5050.67    5.33
  5092.6   19.03 5156.57   20.65 5326.69    19.8 6219.39   23.57 7777.22   23.28
#Mann= 4 ,-1 , 0
-2212.76     .07       0 1983.03     .15       0 4930.07    .032       0
 5156.57     .15       0
#XS Ineff= 8 ,-1
-2212.76    27.3   19.03    27.3 1965.87   22.68 1965.87 2455.33   19.03
 2455.33 4929.87   20.54 4929.87  4947.4   19.03  5092.6 5160.41   19.03
 5160.41 5610.92   20.73 5610.92 7777.22   19.03
Permanent Ineff=
       F       F       F       F       F       F       F       F
#Block Obstruct= 2 ,-1
 -2580.2 1160.41   21.84 7645.05 7849.83   23.82
Bank Sta=4928.55,5156.57
XS Rating Curve= 0
Exp/Cntr=.5,.3

Type RM Length L Ch R = 1 ,26562.23,308.67,335.32,389.95
XS GIS Cut Line= 2
     3221030.152    13810116.314     3210972.188     13809591.95
#Sta/Elev= 30
-2246.54    3.33-2147.24   20.19-2104.24   21.55-1810.41   23.38-1512.86   21.12
-1389.49   23.81 -977.71   21.38 -150.21   24.45 -106.53   27.31    5.26   25.25
   454.9   21.27  858.78   23.59  898.93   20.51 1014.77   20.75  1056.1   23.91
 1177.82   21.74 1983.55   20.87 2367.09   22.06  2524.4   18.23  4233.7   19.41
 4738.44   16.62  4927.4   19.31 4991.48   12.28 5017.45    3.85 5083.29   19.89
 5239.47    18.2 5629.27   21.56 6632.29   21.42 7449.66   25.14 7825.09   23.45
#Mann= 6 ,-1 , 0
-2246.54     .07       0    5.26     .15       0 1177.82     .07       0
 1983.55     .15       0  4927.4    .032       0 5083.29     .15       0
#XS Ineff= 2 ,-1
 5098.02 5397.01   20.04 2225.26 3358.36   19.94
Permanent Ineff=
       F       F
#Block Obstruct= 3 ,-1
-2320.82 1829.35   21.46 7453.92 7890.79   25.15 7467.58 7808.87   24.98
Bank Sta=4927.4,5083.29
XS Rating Curve= 0
Exp/Cntr=.3,.1

Type RM Length L Ch R = 1 ,26226.91,11.42,10,10.38
XS GIS Cut Line= 4
     3219613.977    13810007.012     3213937.997    13809435.357
     3213826.018    13809398.118     3210999.509    13808936.575
#Sta/Elev= 30
 -763.59   22.87  -124.8   24.57  448.53    23.2  512.65   21.18    1139    23.6
 1234.34   20.97    2103   21.67 2527.08   22.07 2576.04   19.53 2756.95   17.53
 3518.16   19.77 3637.21   17.28 3695.84   19.25 4686.66   18.95 4763.21   17.47
 4868.86   19.96 4871.88   19.92 4941.02   17.66 4979.32    3.75 4992.62    3.89
 5058.98   18.79 5080.94    19.7 5172.78   20.02 5236.02   17.38 5566.95   20.82
  6239.4   20.02 6617.47   24.11 6848.72   21.65 7030.99   23.62 7923.06   22.24
#Mann= 5 ,-1 , 0
 -763.59     .15       0 1234.34     .07       0    2103     .15       0
 4868.86    .032       0 5080.94     .15       0
#XS Ineff= 2 ,-1
 5171.51 5448.56   20.04 2522.82 4867.64   19.92
Permanent Ineff=
       F       F
#Block Obstruct= 1 ,-1
   59.16 1697.38   22.05
Bank Sta=4871.88,5080.94
XS Rating Curve= 0
Exp/Cntr=.5,.3

Type RM Length L Ch R = 1 ,26216.9 ,98.75,100.13,99.61
XS GIS Cut Line= 4
     3219690.437    13809981.525     3213939.893    13809425.449
     3213827.964    13809388.226     3210999.509    13808923.831
#Sta/Elev= 30
 -835.26    22.3 -369.01   22.37 -122.59   24.59   35.86   21.88  912.56   20.71
 1157.53   23.54 1267.54   21.21 2056.08   21.91 2532.94   22.04 2579.88   19.45
 2760.72   17.39 3516.06   19.85 3643.76   17.28 3696.75      19 3920.09   17.83
 4128.38   19.51 4768.03   17.39 4877.27   19.93 4941.02   17.66 4979.32    3.75
 4992.62    3.89 5058.98   18.79 5140.79   20.28 5234.11   17.37 5549.91   20.66
 6279.02   20.14 6621.95   24.15  6862.9   21.69 7028.99   23.54 7926.39   22.41
#Mann= 5 ,-1 , 0
 -835.26     .15       0 1267.54     .07       0 2056.08     .15       0
 4877.27    .032       0 5140.79     .15       0
#XS Ineff= 6 ,-1
 -835.26 2493.74      17 2493.74 4882.82   19.83 4882.82 4941.02      17
 5058.98 5139.51      17 5139.51 5507.48   20.28 5507.48 7926.39      17
Permanent Ineff=
       F       F       F       F       F       F
#Block Obstruct= 2 ,-1
 -168.37  1640.5   21.94 5846.71 6207.46   19.82
Bank Sta=4877.27,5140.79
XS Rating Curve= 0
Exp/Cntr=.5,.3

Type RM Length L Ch R = 3 ,26166.84,,,
BEGIN DESCRIPTION:
Wooden Bridge at Catlett
END DESCRIPTION:
Bridge Culvert--1,0,-1,-1, 0
Deck Dist Width WeirC Skew NumUp NumDn MinLoCord MaxHiCord MaxSubmerge Is_Ogee
58,7,2.6,0, 3, 3, , , .95, 0, 0,0,,
    4907    4952    5066
   19.18   18.98    19.1
           17.85      18
    4907    4952    5066
   19.18   18.98    19.1
           17.85      18
Pier Skew, UpSta & Num, DnSta & Num=  ,4961, 2 ,4961, 2 , 0 , 0 , 0 ,,
       1       1
       0      18
       1       1
       0      18
Pier Skew, UpSta & Num, DnSta & Num=  ,4980.5, 2 ,4980.5, 2 , 0 , 0 , 0 ,,
       1       1
       0      18
       1       1
       0      18
Pier Skew, UpSta & Num, DnSta & Num=  ,4999, 2 ,4999, 2 , 0 , 0 , 0 ,,
       1       1
       0      18
       1       1
       0      18
Pier Skew, UpSta & Num, DnSta & Num=  ,5018, 2 ,5018, 2 , 0 , 0 , 0 ,,
       1       1
       0      18
       1       1
       0      18
Pier Skew, UpSta & Num, DnSta & Num=  ,5037, 2 ,5037, 2 , 0 , 0 , 0 ,,
       1       1
       0      18
       1       1
       0      18
BR Coef=-1 , 1 , 1 ,1.25, 0 ,,,.8,0,1.2,0,
WSPro=,,,, 1 ,,,, 0 ,,,, 0 ,,,,-1 ,-1 ,-1 , 0 , 0 , 0 , 0 , 0
BC Design=,, 0 ,, 0 ,,,,,,
BC HTab HWMax=24.59

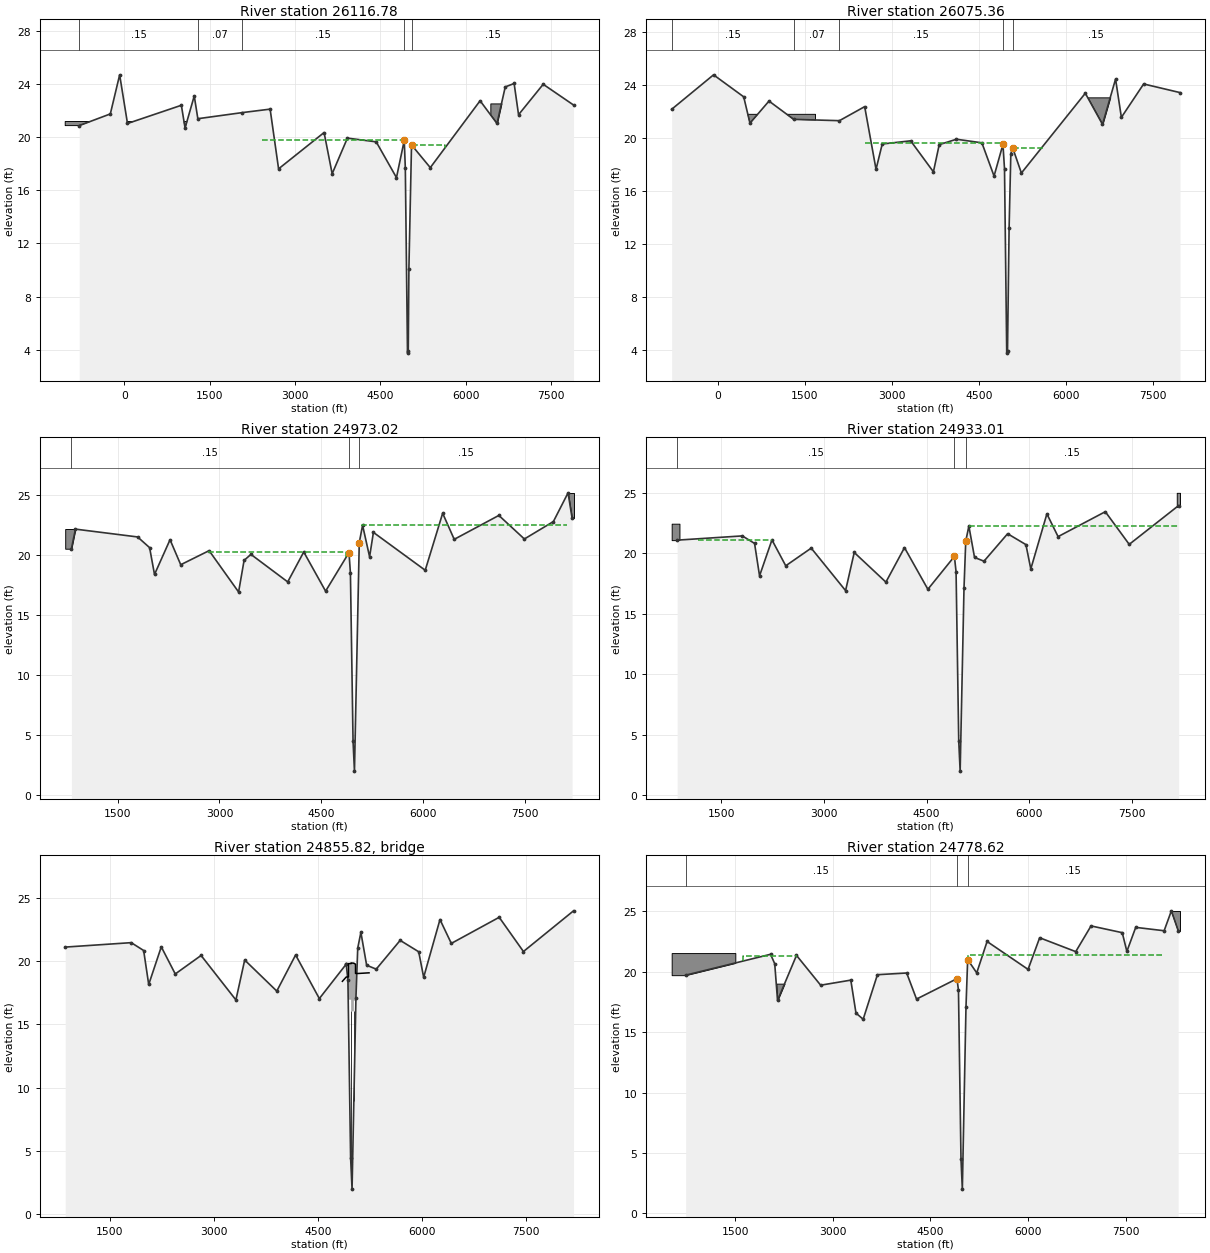
Type RM Length L Ch R = 1 ,26116.78,42.59,41.42,41.16
XS GIS Cut Line= 4
     3219677.694    13809905.065     3213974.628    13809331.442
     3213847.424    13809289.313     3211050.483    13808860.115
#Sta/Elev= 30
 -795.57   20.86 -248.18   21.74  -84.08   24.68    53.7   21.02 1001.38   22.39
  1066.6   20.68 1228.03   23.09 1291.36   21.38 2073.95   21.84 2562.83    22.1
 2711.61   17.61    3512   20.34 3654.14   17.24  3922.1   19.92 4428.95   19.64
 4785.38   16.95 4922.29   19.75 4941.02   17.66 4979.32    3.75 4992.62    3.89
    5004   10.11    5050   19.41 5380.19    17.7 6256.38   22.73 6553.72   21.02
 6698.72   23.77 6855.01   24.03 6932.76   21.68 7366.33   23.97 7899.95   22.41
#Mann= 5 ,-1 , 0
 -795.57     .15       0 1291.36     .07       0 2073.95     .15       0
 4922.29    .032       0    5050     .15       0
#XS Ineff= 5 ,-1
 2415.32 4920.92   19.79 4920.92 4941.02      17    5050 5053.03      17
 5053.03 5633.95   19.42 5633.95 7899.95      17
Permanent Ineff=
       F       F       F       F       F
#Block Obstruct= 2 ,-1
-1041.84  1441.3   21.17 6436.56 6689.17   22.53
Bank Sta=4922.29,5050
XS Rating Curve= 0
Exp/Cntr=.5,.3

Type RM Length L Ch R = 1 ,26075.36,1082.52,1102.34,1103.6
XS GIS Cut Line= 4
     3219690.437    13809854.092     3213988.456    13809291.742
     3213855.208    13809249.748     3210999.509    13808809.142
#Sta/Elev= 30
 -793.98   22.15  -72.38   24.75  447.01   23.09  555.13    21.1  882.92   22.77
 1308.15   21.39 2096.45   21.29 2531.48   22.35 2727.31   17.62 2834.13   19.53
 3323.81   19.77 3716.01   17.43 3816.02   19.48  4112.4   19.89 4551.12   19.62
 4760.88   17.11 4914.17    19.5 4941.02   17.66 4979.32    3.75 4992.62    3.89
    5020   13.16    5050   18.79 5080.94   19.25 5232.04   17.34 6333.21   23.36
 6629.46   21.01 6854.67   24.43 6954.81   21.54 7338.66   24.06 7964.87   23.41
#Mann= 5 ,-1 , 0
 -793.98     .15       0 1308.15     .07       0 2096.45     .15       0
 4914.17    .032       0 5080.94     .15       0
#XS Ineff= 2 ,-1
  2543.8 4902.98   19.63 5081.19 5644.35   19.25
Permanent Ineff=
       F       F
#Block Obstruct= 2 ,-1
-1095.82 1684.21   21.77  6350.4 6771.33   23.05
Bank Sta=4914.17,5080.94
XS Rating Curve= 0
Exp/Cntr=.3,.1

Type RM Length L Ch R = 1 ,24973.02,41.69,40.01,41.18
XS GIS Cut Line= 4
     3218404.329    13808956.751     3214335.475    13808246.814
     3214246.564    13808215.584     3211132.621    13807674.557
#Sta/Elev= 30
  816.31    20.5  875.36   22.13 1792.17   21.48 1969.34   20.59 2041.71   18.36
 2270.79   21.25 2428.48   19.17  2847.4   20.34  3282.1    16.9 3362.95   19.53
 3463.88   20.03 4006.65   17.74 4243.07   20.23 4565.37   16.97 4910.56   20.18
 4931.53   18.47 4970.38    4.49 4991.14       2    5062   21.01 5111.01   22.45
 5214.33   19.83 5270.75   21.86 6034.92   18.71 6292.22   23.45 6462.64   21.28
 7121.06   23.27 7497.55   21.31  7925.6   22.76 8142.05   25.15 8201.46   23.04
#Mann= 3 , 0 , 0
  816.31     .15       0 4910.56    .032       0    5062     .15       0
#XS Ineff= 3 ,-1
 5109.21 8119.45   22.47 1771.33 2273.04    21.2 2836.18 4873.72   20.19
Permanent Ineff=
       F       F       F
#Block Obstruct= 2 ,-1
  724.43   877.9   22.14 8141.69 8222.67   25.12
Bank Sta=4910.56,5062
XS Rating Curve= 0
Exp/Cntr=.5,.3

Type RM Length L Ch R = 1 ,24933.01,154.24,154.39,152.25
XS GIS Cut Line= 4
     3218376.456    13808897.749     3214343.572    13808207.262
     3214254.381    13808175.934     3211164.392    13807634.843
#Sta/Elev= 30
  858.78   21.09 1809.87   21.44 1988.97   20.82 2061.75   18.14 2242.94   21.11
 2444.31   18.97 2816.26   20.43 3318.07   16.92 3444.48   20.07 3906.95   17.62
 4178.15   20.47  4519.9   17.03 4906.48   19.74 4907.14   19.75 4931.53   18.47
 4970.38    4.49 4991.14       2 5047.27   17.11 5073.01   21.01 5118.43   22.25
 5201.31   19.66 5339.29   19.35  5684.3   21.62 5951.59   20.72 6022.76   18.71
 6257.84   23.26 6421.19   21.38 7110.96   23.44 7460.12   20.74 8181.89   23.95
#Mann= 3 ,-1 , 0
  858.78     .15       0 4906.48    .032       0 5073.01     .15       0
#XS Ineff= 4 ,-1
 5119.45 8181.89   22.22  1161.6 2241.96   21.11 2241.96 4900.85   19.64
 5047.27 5119.45   17.11
Permanent Ineff=
       F       F       F       F
#Block Obstruct= 2 ,-1
  778.53  892.12   22.45 8154.03 8201.55      25
Bank Sta=4907.14,5073.01
XS Rating Curve= 0
Exp/Cntr=.5,.3

Type RM Length L Ch R = 3 ,24855.82,,,
BEGIN DESCRIPTION:
Hillridge Drive
END DESCRIPTION:
Bridge Culvert--1,0,-1,-1, 0
Deck Dist Width WeirC Skew NumUp NumDn MinLoCord MaxHiCord MaxSubmerge Is_Ogee
50,40,2.6,0, 12, 12, , , .95, 0, 0,0,,
    4852 4907.11 4939.21 4939.21 4977.99    4978    5017 5017.01 5041.07 5041.08
 5084.56    5236
   18.39   18.73   18.73   19.79   19.79   19.84   19.82   19.82   19.74   19.01
   19.01   19.06
                           16.94   16.94   16.02   16.02   16.87   16.84
                
    4852 4907.11 4939.21 4939.21 4977.99    4978    5017 5017.01 5041.07 5041.08
 5084.56    5236
   18.39   18.73   18.73   19.79   19.79   19.84   19.82   19.82   19.74   19.01
   19.01   19.06
                           16.94   16.94   16.02   16.02   16.87   16.84
                
Pier Skew, UpSta & Num, DnSta & Num=  ,4978, 2 ,4978, 2 , 0 , 0 , 0 ,,
     1.6     1.6
       0      18
     1.6     1.6
       0      18
Pier Skew, UpSta & Num, DnSta & Num=  ,5017, 2 ,5017, 2 , 0 , 0 , 0 ,,
     1.6     1.6
       0      18
     1.6     1.6
       0      18
BR Coef=-1 , 1 , 0 ,, 0 ,,,.8,0,1.2,0,
WSPro=,,,, 1 ,,,, 0 ,,,, 0 ,,,,-1 ,-1 ,-1 , 0 , 0 , 0 , 0 , 0
BC Design=,, 0 ,, 0 ,,,,,,
BC HTab HWMax=25.01

Type RM Length L Ch R = 1 ,24778.62,179.26,181.25,183.12
XS GIS Cut Line= 4
     3218550.641    13808761.668      3214403.25    13808064.068
     3214300.168    13808029.398     3211088.717    13807493.628
#Sta/Elev= 30
  737.96   19.72 2043.52   21.45 2107.21   20.67 2150.57   17.63  2441.9   21.36
 2813.31   18.89 3276.69   19.31 3356.31   16.58 3466.85   16.07 3685.81   19.76
 4135.68    19.9 4286.99   17.74 4908.89   19.43 4931.53   18.47 4970.38    4.49
 4991.14       2 5047.27   17.11 5073.01   21.01 5212.19   19.91 5371.55   22.51
  6001.5    20.2 6179.57   22.82 6734.26   21.67 6969.34    23.8 7449.13   23.24
 7520.02   21.69 7656.09   23.68 8092.73    23.4 8204.35   25.05  8308.2   23.42
#Mann= 3 , 0 , 0
  737.96     .15       0 4908.89    .032       0 5073.01     .15       0
#XS Ineff= 4 ,-1
 5085.32 8065.98   21.39 1620.44 2442.93    21.3 2442.93 4908.76   19.33
 5047.27 5085.32   17.11
Permanent Ineff=
       F       F       F       F
#Block Obstruct= 3 ,-1
  523.32 1501.71   21.55 2053.36 2390.78   19.02 8204.48 8336.69   25.03
Bank Sta=4908.89,5073.01
XS Rating Curve= 0
Exp/Cntr=.5,.3

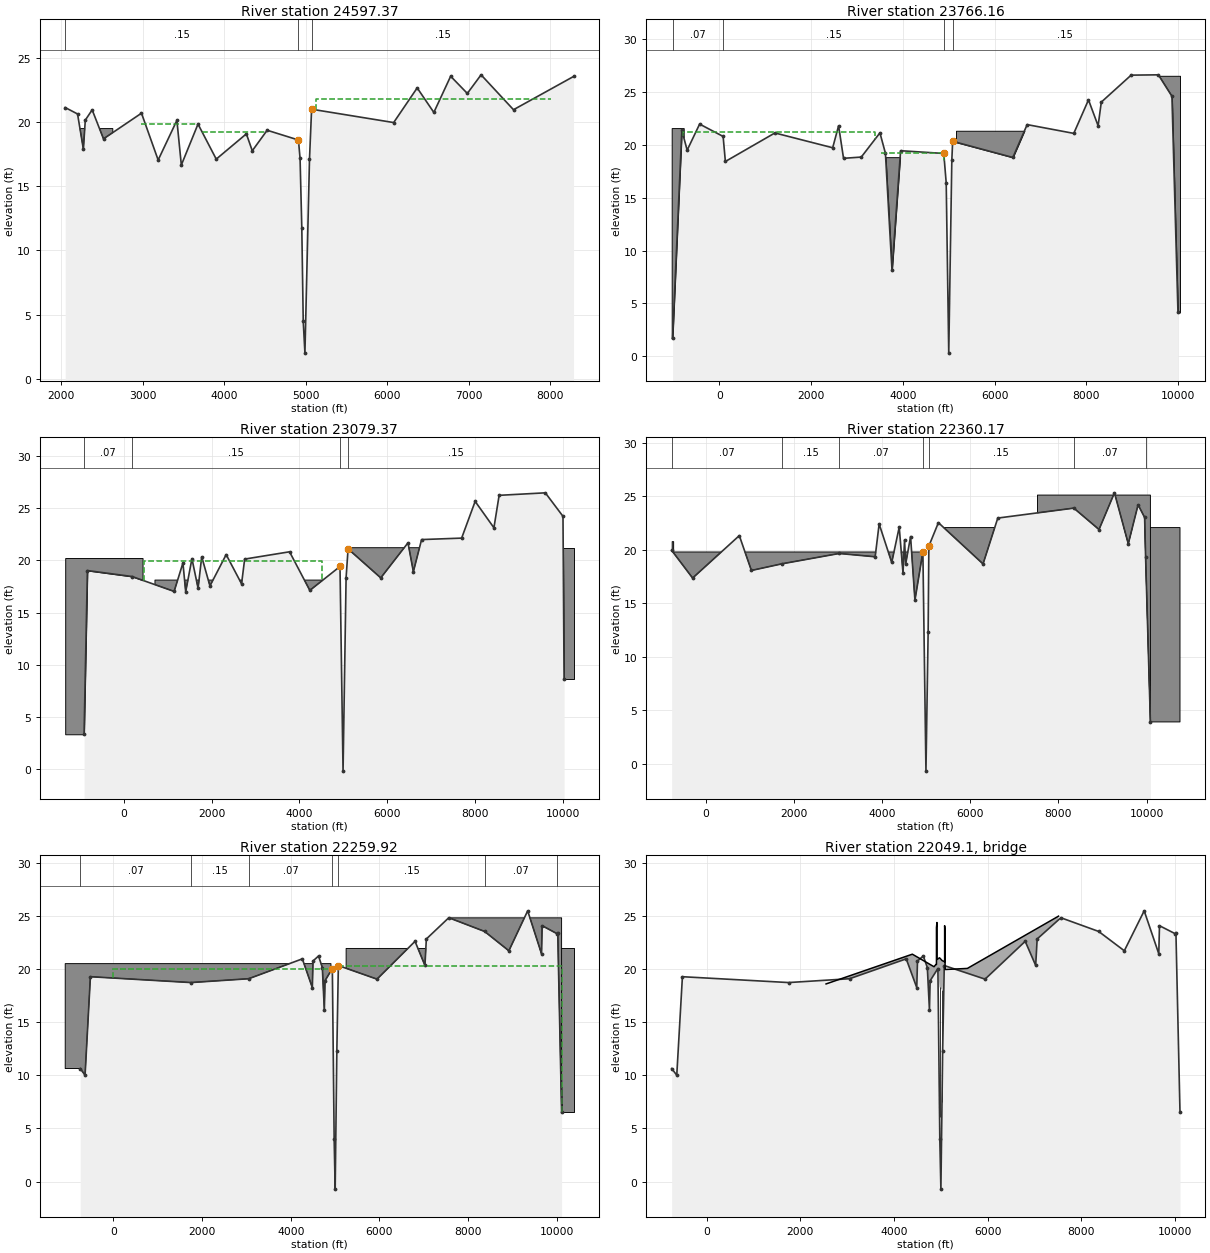
Type RM Length L Ch R = 1 ,24597.37,877.3,831.22,784.53
XS GIS Cut Line= 4
     3217312.121    13808389.409     3214468.519    13807894.538
     3214336.199    13807850.968     3211161.874    13807347.316
#Sta/Elev= 30
 2048.63   21.14 2200.06   20.64 2271.69    17.9 2295.27   20.16 2379.54   20.96
 2518.74    18.7  2984.9    20.7 3189.63   17.05 3419.63   20.14 3474.08   16.66
 3678.73   19.85  3902.6   17.12 4272.49   19.09 4344.83   17.77 4527.66   19.37
 4911.62   18.61 4931.53   17.17 4952.73   11.79 4970.38    4.49 4991.14       2
 5047.27   17.11 5073.01   21.01 6080.47   19.97 6369.18   22.67  6573.7   20.76
 6779.99   23.58 6984.65   22.24 7153.36   23.69  7551.4   20.97 8288.31   23.56
#Mann= 3 , 0 , 0
 2048.63     .15       0 4911.62    .032       0 5073.01     .15       0
#XS Ineff= 3 ,-1
 5121.73 8012.51   21.78 2973.01 3672.06   19.83 3738.19 4522.27   19.23
Permanent Ineff=
       F       F       F
#Block Obstruct= 2 ,-1
 2170.04 2632.93    19.5 5109.47 6800.38   18.76
Bank Sta=4911.62,5073.01
XS Rating Curve= 0
Exp/Cntr=.3,.1

Type RM Length L Ch R = 1 ,23766.16,685.81,686.79,684.14
XS GIS Cut Line= 4
     3220620.326    13807349.111     3214662.848    13807083.282
     3214540.484    13807081.409     3209620.066    13806736.465
#Sta/Elev= 30
-1021.49     1.7 -819.59   21.38  -703.9    19.5 -432.33   21.97   80.34    20.8
  129.11   18.43  1208.8   21.13  2468.8   19.73 2597.63   21.81 2705.44   18.73
 3092.13   18.85 3499.03   21.14 3618.64   19.21 3762.07    8.14  3949.7   19.45
 4890.85   19.19 4943.81   16.41 4999.27      .3 5066.19   18.54 5084.45   20.34
 6397.28   18.81 6708.71   21.92 7725.25   21.09 8045.92   24.26 8255.66   21.81
 8325.54   24.05 8975.46    26.6 9569.03   26.63 9865.02    24.6 9996.79    4.15
#Mann= 4 ,-1 , 0
-1021.49     .07       0   80.34     .15       0 4890.85    .032       0
 5084.45     .15       0
#XS Ineff= 2 ,-1
 -785.43 3392.71   21.21 3528.33 4904.85   19.27
Permanent Ineff=
       F       F
#Block Obstruct= 4 ,-1
-1041.53 -779.52   21.59 3563.48    3974   18.84 5157.89 6971.66   21.34
 9569.0110040.97   26.54
Bank Sta=4890.85,5084.45
XS Rating Curve= 0
Exp/Cntr=.3,.1

Type RM Length L Ch R = 1 ,23079.37,714.99,719.2,719.12
XS GIS Cut Line= 4
     3220522.248    13806666.068     3214687.106    13806397.572
     3214558.664    13806393.712     3209594.411    13806129.293
#Sta/Elev= 30
  -908.2    3.33 -831.98   19.02  185.92   18.45 1144.58   17.02 1345.28   19.75
 1408.29   16.99 1550.71   20.16 1690.65   17.32 1773.18   20.34 1960.93   17.55
 2330.67   20.55 2681.69   17.75  2752.3   20.12  3775.7   20.82 4237.58   17.12
 4925.25   19.41 4994.92     -.2 5064.25   18.33 5109.42    21.1 5854.43   18.32
 6475.48   21.68 6597.58   18.91 6784.78   21.99 7697.86   22.13 8006.03   25.65
 8433.91   23.12 8552.46   26.23 9605.56   26.4710007.94   24.2210032.91    8.62
#Mann= 4 ,-1 , 0
  -908.2     .07       0  185.92     .15       0 4925.25    .032       0
 5109.42     .15       0
#XS Ineff= 1 ,-1
  451.22 4520.97   19.97
Permanent Ineff=
       F
#Block Obstruct= 3 ,-1
-1338.07  424.91   20.22  707.62 4530.15   18.11 5111.1810248.35   21.21
Bank Sta=4925.25,5109.42
XS Rating Curve= 0
Exp/Cntr=.3,.1

Type RM Length L Ch R = 1 ,22360.17,100.15,100.25,99.73
XS GIS Cut Line= 4
     3220417.164    13806007.543     3214684.157    13805678.586
     3214631.128    13805674.408     3209577.307    13805470.809
#Sta/Elev= 30
 -768.67   19.93 -293.77   17.34  764.87   21.31 1038.76   18.05 1727.66   18.67
 3030.08   19.64 3844.92   19.33 3935.07    22.4 4220.54    18.8  4390.2    22.1
 4475.96   17.83 4511.08    20.9 4536.06   18.65 4647.68   21.22  4746.4   15.27
  4926.7   19.79 4996.35    -.71 5046.03   12.33    5062   20.33  5278.7   22.52
 6290.71   18.66 6624.91   22.95 8348.32   23.88  8920.1   21.88    9270   25.31
 9583.55   20.55 9805.81   24.19 9954.07   23.01 9976.35   19.2810084.89    3.89
#Mann= 7 ,-1 , 0
 -768.67     .07       0 1727.66     .15       0 3030.08     .07       0
  4926.7    .032       0    5062     .15       0 8348.32     .07       0
 9976.35     .15       0
#Block Obstruct= 4 ,-1
 -900.31 4922.25   19.78 -768.67 -735.01   20.79 5286.8810756.02   22.06
 7524.4610084.89    25.1
Bank Sta=4926.7,5062
XS Rating Curve= 0
Exp/Cntr=.5,.3

Type RM Length L Ch R = 1 ,22259.92,420.78,421.7,427.64
XS GIS Cut Line= 4
     3220403.153    13805905.963     3214690.927    13805578.809
     3214637.105    13805574.569     3209568.755     13805376.74
#Sta/Elev= 30
  -743.9   10.64 -635.14   10.01 -514.73   19.28 1751.09   18.73 3052.82   19.09
 4261.29   20.96 4486.65   18.25 4501.68   20.76 4626.26   21.23 4712.02   20.14
  4757.1   16.14 4772.12    18.9 4937.39   20.05  4978.4    3.98 5001.35    -.71
    5039   12.33    5073   20.33 5943.85   19.05 6800.74   22.61 7024.14   20.34
 7055.66   22.83 7561.68   24.83 8368.24   23.54 8915.58   21.72  9339.5   25.48
 9651.14   21.44 9666.15   24.08 9995.41   23.3410016.88   23.4410103.88    6.51
#Mann= 7 ,-1 , 0
  -743.9     .07       0 1751.09     .15       0 3052.82     .07       0
 4937.39    .032       0    5073     .15       0 8368.24     .07       0
 9995.41     .15       0
#XS Ineff= 2 , 0
       0 4937.39   20.05    5073       0   20.33
Permanent Ineff=
       F       F
#Block Obstruct= 3 ,-1
-1082.66 4906.34   20.51 5247.87 10372.8   21.94 7562.3710103.88   24.82
Bank Sta=4937.39,5073
XS Rating Curve= 0
Exp/Cntr=.5,.3

Type RM Length L Ch R = 3 ,22049.1 ,,,
BEGIN DESCRIPTION:
Fairmont Parkway
END DESCRIPTION:
Bridge Culvert--1,0,-1,-1, 0
Deck Dist Width WeirC Skew NumUp NumDn MinLoCord MaxHiCord MaxSubmerge Is_Ogee
80,157,2.6,0, 17, 17, , , .95, 0, 0,0,,
    2551    4392  4854.2  4894.2 4906.69  4906.7  4916.6 4916.61  4972.4    5025
    5081 5081.01    5091 5091.01    5113    5566    7512
    18.6    21.4   20.22   20.43   20.43    23.9   24.38    20.9   21.06   20.81
   20.68   24.08   23.57   19.96   19.96   20.06   24.98
                                                           18.18   18.29   18.04
   17.84
    2551    4392  4854.2  4894.2 4906.69  4906.7  4916.6 4916.61  4972.4    5025
    5081 5081.01    5091 5091.01    5113    5566    7512
    18.6    21.4   20.22   20.43   20.43    23.9   24.38    20.9   21.06   20.81
   20.68   24.08   23.57   19.96   19.96   20.06   24.98
                                                           18.18   18.29   18.04
   17.84
Pier Skew, UpSta & Num, DnSta & Num=  ,4973, 4 ,4973, 4 , 3 , 3 , 0 ,,
     1.5     1.5     2.6     2.6
       0   15.49   15.49   18.29
     1.5     1.5     2.6     2.6
       0   15.49   15.49   18.29
Pier Skew, UpSta & Num, DnSta & Num=  ,5025, 4 ,5025, 4 , 3 , 3 , 0 ,,
     1.5     1.5     2.6     2.6
       0   15.49   15.49   18.29
     1.5     1.5     2.6     2.6
       0   15.49   15.49   18.29
BR Coef=-1 , 1 , 0 ,, 0 ,,,.8,0,2,0,
WSPro=,,,, 1 ,,,, 0 ,,,, 0 ,,,,-1 ,-1 ,-1 , 0 , 0 , 0 , 0 , 0
BC Design=,, 0 ,, 0 ,,,,,,
BC HTab HWMax=25.48

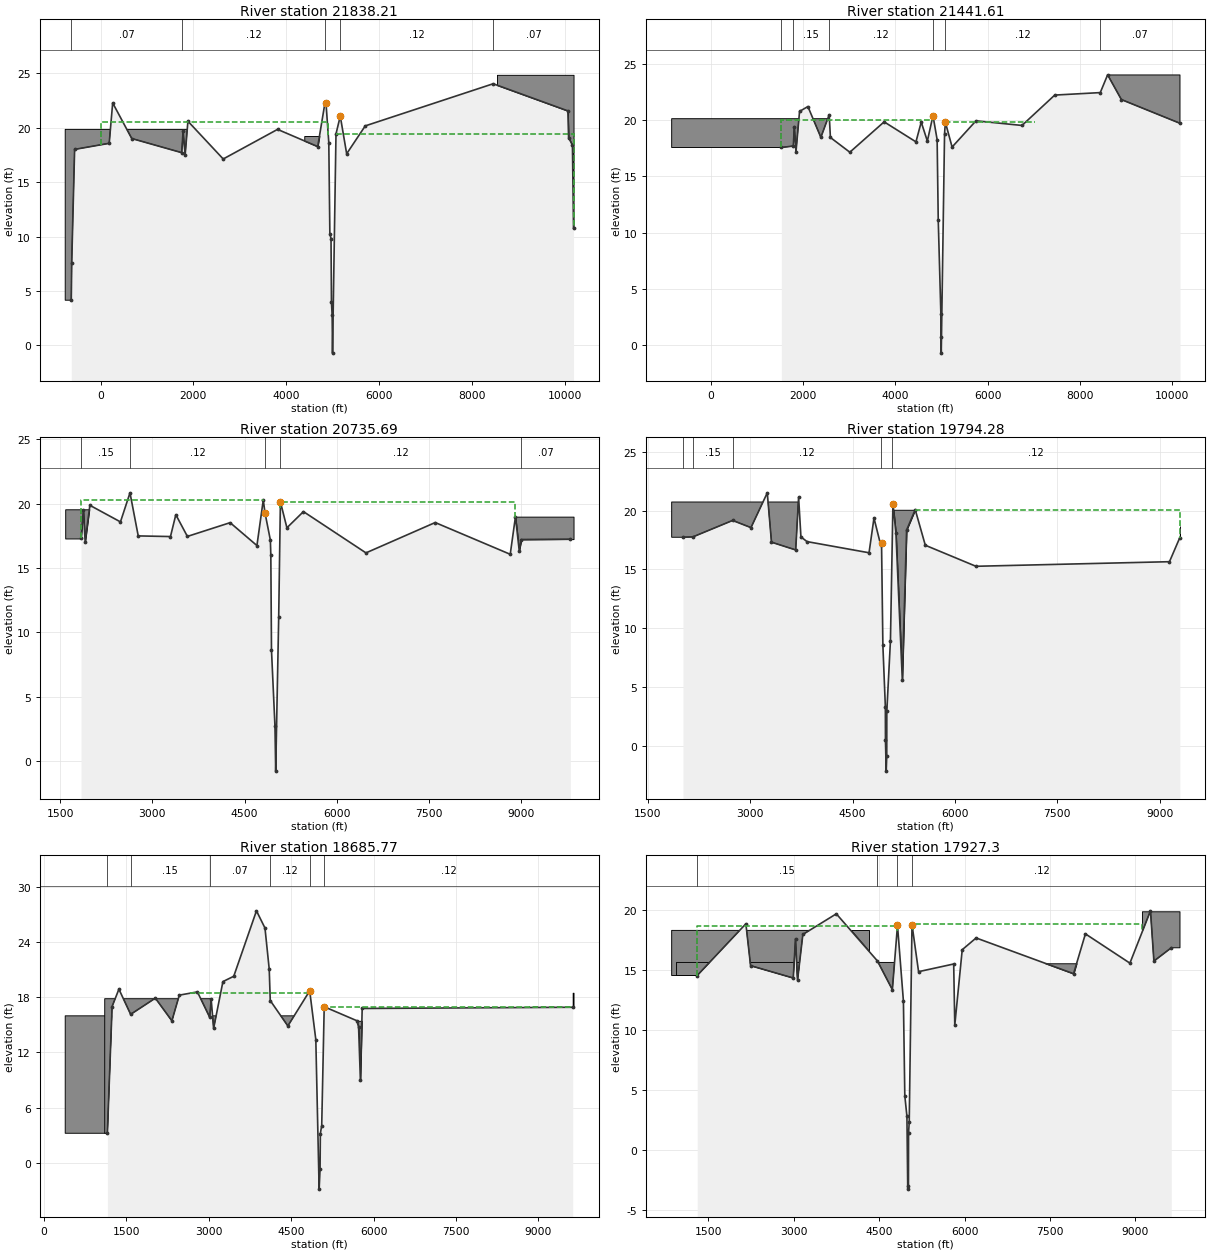
Type RM Length L Ch R = 1 ,21838.21,394.33,396.6,397.96
XS GIS Cut Line= 6
     3220329.594    13805349.019     3219485.059     13805324.51
     3218361.751    13805401.449     3211375.697    13804939.815
     3210637.083     13804770.55     3209551.652    13804718.257
#Sta/Elev= 30
 -630.03    4.15 -620.17    7.61 -557.85      18   187.1   18.56  261.75   22.27
  672.45      19 1749.63    17.7 1777.35   19.65 1822.45   17.49 1881.97   20.59
 2642.35   17.12 3812.45   19.84 4677.58   18.26 4837.89   22.39 4855.64   22.27
    4916   18.62    4939   10.25    4964    9.81  4973.4    3.98 4988.22    2.76
 4996.35    -.71    5071   19.42 5163.25   21.06  5300.9    17.6 5700.89   20.16
  8455.9   24.03 10063.9   21.5410080.29   19.0910162.87   18.3810186.55   10.76
#Mann= 5 ,-1 , 0
 -630.03     .07       0 1749.63     .12       0 4837.89    .032       0
 5163.25     .12       0  8455.9     .07       0
#XS Ineff= 2 , 0
       0 4904.16   20.51    5071       0   19.42
Permanent Ineff=
       F       F
#Block Obstruct= 3 ,-1
 -760.49 1868.28   19.84 4387.64 4828.13   19.23 8537.3910186.55   24.85
Bank Sta=4855.64,5163.25
XS Rating Curve= 0
Exp/Cntr=.5,.3

Type RM Length L Ch R = 1 ,21441.61,627.1,705.92,841.71
XS GIS Cut Line= 6
     3218220.625    13805026.422      3217431.56    13804953.021
     3216780.123    13804907.145     3211433.928    13804542.791
     3210692.368     13804372.85     3209611.514    13804316.326
#Sta/Elev= 30
 1528.13   17.57 1787.55    17.7  1808.8   19.43 1845.11   17.19 1922.66   20.78
 2103.59   21.21 2384.95   18.47  2565.8   20.49 2591.67   18.46 3013.37   17.15
 3757.42   19.85 4447.72   18.07 4561.87   19.83 4694.92   18.14 4816.88    20.4
 4906.95   18.27    4931   11.14 4988.22    2.76 4989.63     .69 4996.35    -.71
    5068    18.8  5085.8   19.81  5231.6   17.61 5749.04   19.94 6748.05   19.53
 7458.29   22.23 8445.92   22.45 8605.61   24.03 8903.88   21.8310175.36   19.72
#Mann= 6 ,-1 , 0
 1528.13     .07       0 1787.55     .15       0  2565.8     .12       0
 4816.88    .032       0    5068     .12       0 8445.92     .07       0
#XS Ineff= 2 ,-1
 1528.13 4791.81      20 5092.15 7030.72   19.81
Permanent Ineff=
       F       F
#Block Obstruct= 2 ,-1
 -851.47 2561.64   20.13 8600.6810175.36   24.02
Bank Sta=4816.88,5085.8
XS Rating Curve= 0
Exp/Cntr=.3,.1

Type RM Length L Ch R = 1 ,20735.69,882.59,941.41,920.91
XS GIS Cut Line= 4
     3217975.913    13804919.128     3214999.532    13804134.173
     3214862.176     13804041.74     3210678.633    13801860.987
#Sta/Elev= 30
 1839.28   17.29 1875.22   19.47 1906.25   17.04 1982.67   19.87 2480.23   18.58
 2635.43   20.84 2769.54   17.49 3294.17   17.44 3381.18   19.14  3569.4   17.45
 4264.82   18.52 4700.95   16.74 4804.21   20.29 4832.24   19.28 4919.69   17.16
    4927   15.97 4937.73    8.61 4994.28    2.69 5006.24     -.8 5055.01   11.16
 5082.78   20.14  5188.7   18.12 5457.67   19.38 6474.81   16.17 7601.73   18.53
 8822.37   16.06 8907.32   18.98 8969.06   16.33 9004.65   17.21  9800.8   17.24
#Mann= 5 ,-1 , 0
 1839.28     .15       0 2635.43     .12       0 4832.24    .032       0
 5082.78     .12       0 9004.65     .07       0
#XS Ineff= 2 ,-1
 1839.28 4800.91   20.25 5081.38 8901.95   20.14
Permanent Ineff=
       F       F
#Block Obstruct= 3 ,-1
 1581.34  1990.9   19.56 1681.91 4830.83   16.52 8907.64 9852.32   18.99
Bank Sta=4832.24,5082.78
XS Rating Curve= 0
Exp/Cntr=.3,.1

Type RM Length L Ch R = 1 ,19794.28,1248.6,1108.51,1005.58
XS GIS Cut Line= 4
     3218101.348    13804732.816      3215541.95    13803367.118
     3215400.314    13803267.327     3211486.048     13801723.36
#Sta/Elev= 30
 2014.38   17.73 2160.02   17.76 2742.58   19.16 3011.16   18.55 3250.07   21.51
 3311.71   17.31 3666.54   16.65 3709.12   21.13 3743.12   17.76 3832.21   17.36
 4741.38   16.41 4813.77   19.36 4912.62   17.07 4924.51   17.26 4944.31    8.52
 4980.52    3.31 4982.01     .45 4992.98   -2.17 5001.19    -.88 5002.02    2.93
 5055.24    8.94 5091.63    20.6 5135.42   18.08 5229.01    5.61 5291.95   18.34
 5418.28   20.08 5566.07   17.05  6307.9   15.26 9144.59   15.65 9296.38    17.7
#Mann= 5 ,-1 , 0
 2014.38     .07       0 2160.02     .15       0 2742.58     .12       0
 4912.62    .032       0 5072.82     .12       0
#XS Ineff= 1 ,-1
  5422.4 9524.97   20.02
Permanent Ineff=
       F
#Block Obstruct= 6 ,-1
 1848.85  3705.8   20.73 1976.61 4845.42    16.1 5091.43 5417.16   20.07
 9296.14 9297.73   18.56 9296.41 9298.79   18.66 9544.94 9296.38   15.45
Bank Sta=4924.51,5091.63
XS Rating Curve= 0
Exp/Cntr=.3,.1

Type RM Length L Ch R = 1 ,18685.77,768.67,758.47,727.58
XS GIS Cut Line= 4
     3219930.276    13802672.889     3216185.636    13802409.266
     3216003.119    13802401.159     3211522.749    13801705.009
#Sta/Elev= 30
 1154.29    3.22 1240.33   16.99 1364.09   18.88 1577.83   16.14 2027.26    17.9
 2328.68   15.44 2464.04   18.23 2793.29   18.58 3017.85   15.81 3043.07   17.81
 3088.18   14.62  3257.6    19.7 3454.72   20.28 3868.06   27.39 4023.04   25.52
 4100.47   21.05 4119.05   17.64 4439.49   14.88 4837.14    18.7 4948.45    13.4
 5009.02   -2.85 5025.96    -.66 5031.08    3.19 5055.88    4.05 5101.35   16.97
 5695.12   15.45 5727.07   14.77 5759.93    9.01 5792.69   16.78 9625.03   16.91
#Mann= 6 ,-1 , 0
 1154.29     .07       0 1577.83     .15       0 3017.85     .07       0
 4119.05     .12       0 4837.14    .032       0 5101.35     .12       0
#XS Ineff= 2 ,-1
 2662.12 4835.04   18.48 5100.55 9625.03   16.97
Permanent Ineff=
       F       F
#Block Obstruct= 5 ,-1
  386.58 4853.47   15.98 1106.01 3046.05   17.84  5694.3 5786.24   15.44
 9624.12 9639.87   18.49 9625.17 9625.17   18.21
Bank Sta=4837.14,5101.35
XS Rating Curve= 0
Exp/Cntr=.3,.1

Type RM Length L Ch R = 1 ,17927.3 ,505.21,505.54,502.43
XS GIS Cut Line= 4
     3219807.679    13801779.678     3216189.436    13801658.438
     3216038.855    13801664.089     3211486.048    13801448.105
#Sta/Elev= 30
 1301.97   14.55 2156.74   18.86 2239.64   15.37 2989.44   14.34  3028.8   17.62
 3064.48   14.16 3157.91   17.97 3745.71   19.69 4466.95   15.77 4730.41   13.37
 4820.47   18.72 4924.66   12.42 4949.16    4.53 4986.27    2.82 5000.78   -3.25
 5013.08   -2.98 5014.72    1.39 5026.73    2.34 5075.34    18.8  5190.9   14.87
 5807.93   15.51 5827.07   10.41 5957.79    16.7  6201.9   17.68 7913.82    14.7
 8122.16   18.02 8903.72   15.58 9265.34   19.94  9325.4   15.75 9630.86   16.86
#Mann= 4 ,-1 , 0
 1301.97     .15       0 4466.95     .07       0 4820.47    .032       0
 5075.34     .12       0
#XS Ineff= 2 ,-1
 1301.97 4812.29   18.68 5087.72 9119.69   18.87
Permanent Ineff=
       F       F
#Block Obstruct= 5 ,-1
  853.24 4323.09   18.31  939.04 4828.79   15.64 5955.75 6012.97   15.65
 5984.07 8168.37   15.57    9124 9783.85   19.86
Bank Sta=4820.47,5075.34
XS Rating Curve= 0
Exp/Cntr=.3,.1