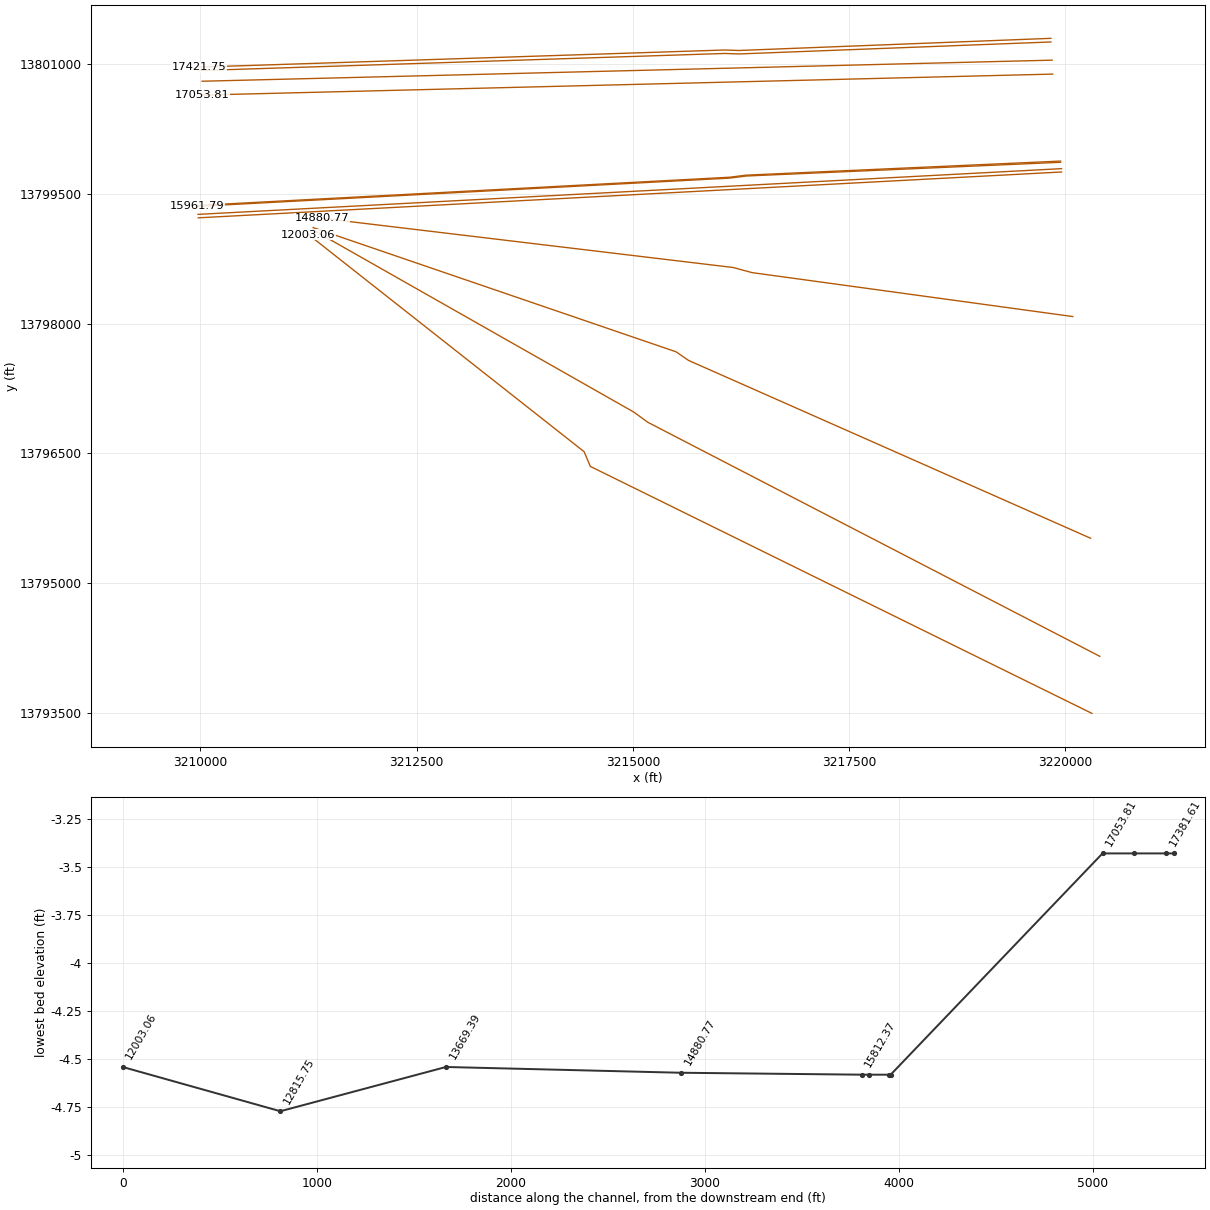
HEC-RAS study B106_00_00.prj: B106-00-00

--- B106_00_00.g03 (geometry) --- (continued)

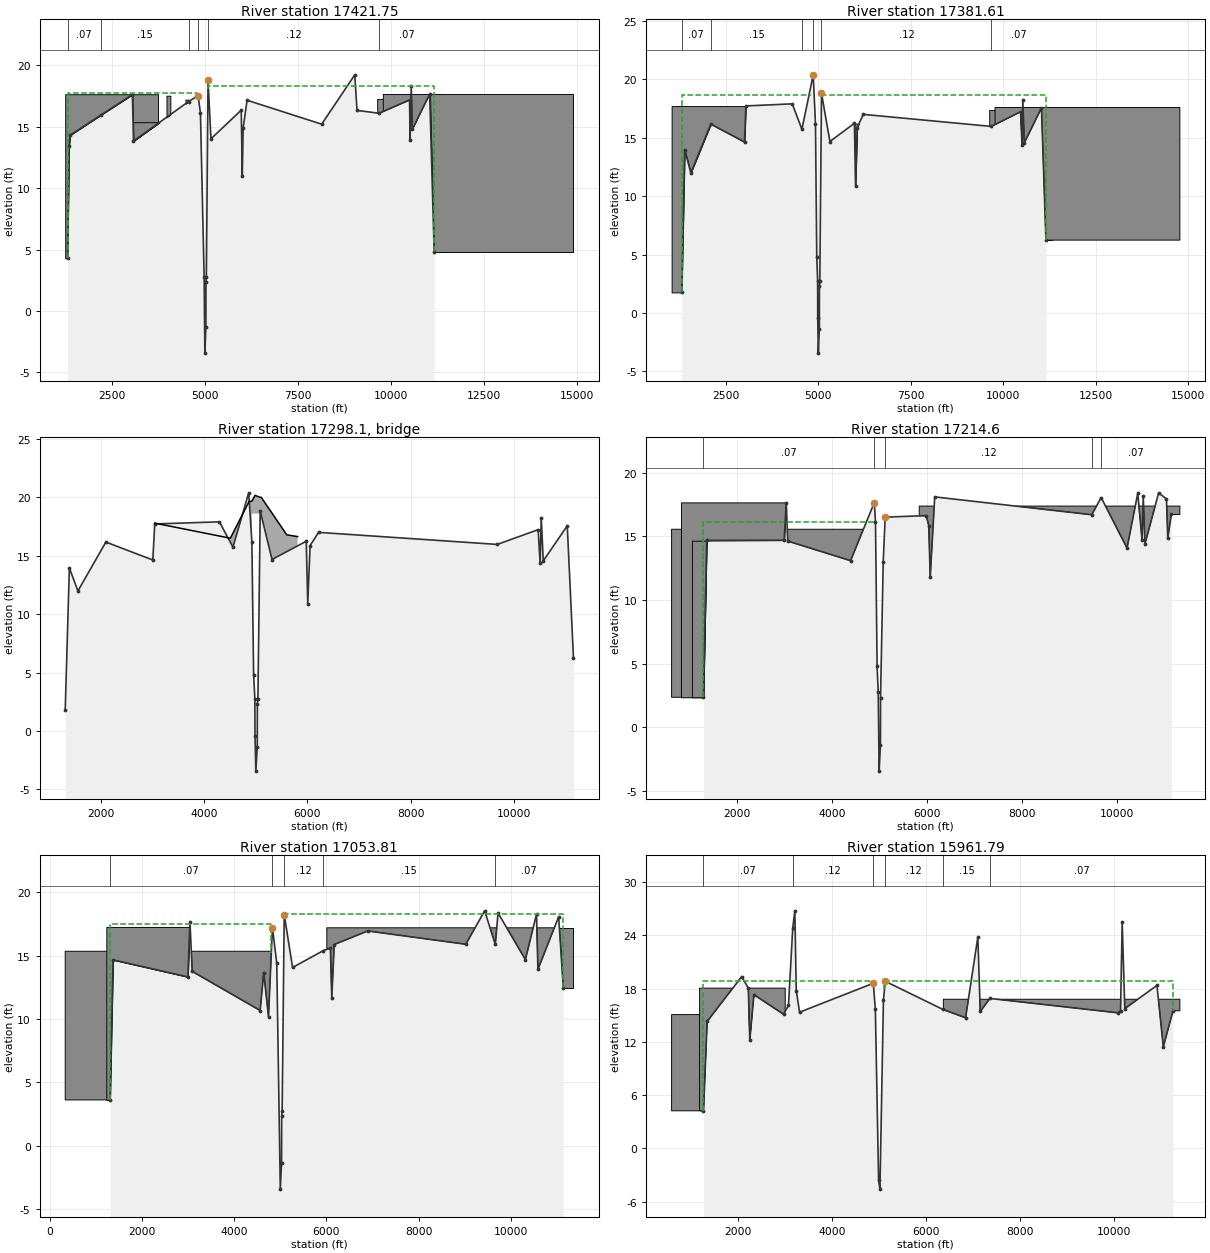
Type RM Length L Ch R = 1 ,17421.75,40.12,40.15,40.01
XS GIS Cut Line= 4
     3219832.198    13801296.293     3216225.488    13801155.856
     3216063.716    13801161.496     3209989.494    13800963.583
#Sta/Elev= 30
 1306.72     4.3 1350.19   13.45 1381.41   14.33 2193.11   15.94 3049.08   17.63
  3079.1   13.85 4556.81   17.06 4813.36   17.55    4877   16.15 4976.54    2.77
  4995.5   -3.43  5023.3   -1.34  5025.1    2.34  5035.7    2.75 5080.99   18.79
 5159.85   14.03 5973.02   16.36 6000.43   10.99 6024.07    14.9 6129.47   17.17
  8133.1   15.22 9022.68   19.24 9082.51   16.34 9678.16   16.1110493.46   17.19
10508.47   13.9410538.49   18.32 10568.5   14.7911033.75   17.6711155.48    4.81
#Mann= 6 ,-1 , 0
 1306.72     .07       0 2193.11     .15       0 4556.81     .07       0
 4813.36    .032       0 5080.99     .12       0 9678.16     .07       0
#XS Ineff= 2 ,-1
 1306.72 4791.81   17.78 5093.2811155.48   18.31
Permanent Ineff=
       F       F
#Block Obstruct= 7 ,-1
 1244.91  3736.2   17.66 3071.26  4815.7   15.38 3965.04 4068.66   17.54
 4474.52 4565.19   17.22 6143.34 7440.27   15.62 9638.2111384.83   17.24
 9788.6714896.25   17.64
Bank Sta=4813.36,5080.99
XS Rating Curve= 0
Exp/Cntr=.5,.3

Type RM Length L Ch R = 1 ,17381.61,164.81,167.01,169.8
XS GIS Cut Line= 4
     3219832.198     13801254.26     3216225.561     13801115.83
     3216063.671    13801121.474     3209990.797    13800923.604
#Sta/Elev= 30
 1307.23    1.76 1387.95   13.94 1553.49   11.97 2095.02   16.15 3004.52   14.62
 3042.12    17.7 4295.46   17.88 4556.87   15.71 4862.38   20.36 4924.01   16.15
 4957.78    4.81 4981.54    2.77 4984.69     -.4  5000.5   -3.43  5028.3   -1.34
  5030.1    2.34  5040.7    2.75 5085.99   18.79 5313.96   14.66  5976.5   16.22
 6006.52   10.89 6051.66   15.85 6216.35   16.98  9677.5   15.9510470.28   17.21
10508.91   14.3310530.18   18.2410568.94   14.5411034.19   17.5411154.61    6.23
#Mann= 6 ,-1 , 0
 1307.23     .07       0 2095.02     .15       0 4556.87     .07       0
 4862.38    .032       0 5085.99     .12       0  9677.5     .07       0
#XS Ineff= 2 ,-1
 1307.23 4805.46   18.67 5086.0111154.61   18.66
Permanent Ineff=
       F       F
#Block Obstruct= 5 ,-1
 1033.57 3043.24   17.69 3069.35 4781.02   15.65 5975.19 6115.34   16.19
 9634.3211328.49   17.31 9778.2914776.11   17.57
Bank Sta=4862.38,5085.99
XS Rating Curve= 0
Exp/Cntr=.5,.3

Type RM Length L Ch R = 3 ,17298.1 ,,,
BEGIN DESCRIPTION:
Big Island Slough Railroad Crossing
END DESCRIPTION:
Bridge Culvert--1,0,-1,-1, 0
Deck Dist Width WeirC Skew NumUp NumDn MinLoCord MaxHiCord MaxSubmerge Is_Ogee
102,17,2.6,0, 11, 11, , , .95, 0, 0,0,,
    3042    4507 4868.48    4924 4924.01 4985.31 5073.99    5074  5104.3    5600
    5809
   17.77   16.48   19.61   19.65   19.65   20.14   19.99   19.99   19.98   16.77
   16.62
                       0       0   18.58   18.58   18.58       0       0
        
    3042    4507 4868.48    4924 4924.01 4985.31 5073.99    5074  5104.3    5600
    5809
   17.77   16.48   19.61   19.65   19.65   20.14   19.99   19.99   19.98   16.77
   16.62
                       0       0   18.58   18.58   18.58       0       0
        
Pier Skew, UpSta & Num, DnSta & Num=  ,4952, 4 ,4952, 4 , 3 , 3 , 0 ,,
     1.4     1.4     2.8     2.8
       0   15.76   15.76
     1.4     1.4     2.8     2.8
       0   15.76   15.76
Pier Skew, UpSta & Num, DnSta & Num=  ,4982.175, 4 ,4982.175, 4 , 3 , 3 , 0 ,,
     1.4     1.4     2.8     2.8
       0   15.76   15.76
     1.4     1.4     2.8     2.8
       0   15.76   15.76
Pier Skew, UpSta & Num, DnSta & Num=  ,5012.061, 4 ,5012.061, 4 , 3 , 3 , 0 ,,
     1.4     1.4     2.8     2.8
       0   15.76   15.76
     1.4     1.4     2.8     2.8
       0   15.76   15.76
Pier Skew, UpSta & Num, DnSta & Num=  ,5041.93, 4 ,5041.93, 4 , 3 , 3 , 0 ,,
     1.4     1.4     2.8     2.8
       0   15.76   15.76
     1.4     1.4     2.8     2.8
       0   15.76   15.76
BR Coef=-1 , 1 , 0 ,, 0 ,,,.8,0,1.2,0,
WSPro=,,,, 1 ,,,, 0 ,,,, 0 ,,,,-1 ,-1 ,-1 , 0 , 0 , 0 , 0 , 0
BC Design=,, 0 ,, 0 ,,,,,,
BC HTab HWMax=20.36

Type RM Length L Ch R = 1 ,17214.6 ,160.82,160.78,160.74
XS GIS Cut Line= 2
     3219846.209    13801044.093     3210021.572    13800800.502
#Sta/Elev= 30
  1304.8    2.37 1373.56   14.69 3000.37   14.71 3045.39   17.66 3075.41   14.64
  4395.8    13.1 4894.53   17.67 4919.01   16.15 4952.78    4.81 4976.54    2.77
  4995.5   -3.43  5023.3   -1.34  5025.1    2.34 5080.99      13    5123   16.52
 5987.46   16.64    6038   15.84 6068.38   11.79 6163.05   18.11 9461.75   16.71
 9658.31   18.0610202.59   14.0910427.65   18.3910517.68   14.7310542.66   18.17
 10577.7   14.3910866.34   18.4311030.94   17.9511057.85   14.8611132.46   16.73
#Mann= 5 ,-1 , 0
  1304.8     .07       0 4894.53    .032       0    5123     .12       0
 9461.75     .15       0 9658.31     .07       0
#XS Ineff= 2 ,-1
  1304.8 4919.01   16.15 5125.59 5839.06   16.51
Permanent Ineff=
       F       F
#Block Obstruct= 4 ,-1
  636.72 4830.99   15.57  832.76 3030.72   17.68 1063.37 1374.74   14.67
 5837.4711312.21   17.39
Bank Sta=4894.53,5123
XS Rating Curve= 0
Exp/Cntr=.5,.3

Type RM Length L Ch R = 1 ,17053.81,1077.81,1092.02,1107.07
XS GIS Cut Line= 2
     3219853.215    13800882.964     3210025.503     13800640.55
#Sta/Elev= 30
 1308.57    3.61 1373.47   14.67 2996.14   13.32 3041.16   17.68 3090.05   13.76
 4564.01   10.67 4641.33   13.67 4744.75   10.17 4829.73   17.22 4924.01    14.4
  5000.5   -3.43  5028.3   -1.34  5030.1    2.34  5040.7    2.75 5085.99   18.24
 5266.89   14.07    5929   15.39 6087.08    15.6 6117.09   11.67 6170.85   15.88
 6897.33   16.95 9024.52    15.9  9433.1   18.54 9664.66   15.89 9723.78   18.37
10317.37   14.6910558.44   18.2910588.45   13.9111038.58   18.0711139.27   12.48
#Mann= 5 ,-1 , 0
 1308.57     .07       0 4829.73    .032       0 5085.99     .12       0
    5929     .15       0 9664.66     .07       0
#XS Ineff= 2 ,-1
 5092.1511139.27   18.26 1308.57 4805.46   17.52
Permanent Ineff=
       F       F
#Block Obstruct= 3 ,-1
  335.02    4837   15.35 1226.88 3043.37   17.27 6010.1411359.95    17.2
Bank Sta=4829.73,5085.99
XS Rating Curve= 0
Exp/Cntr=.3,.1

Type RM Length L Ch R = 1 ,15961.79,10.22,10.06,10.01
XS GIS Cut Line= 4
     3219944.287    13799877.664     3216310.869    13799714.972
     3216117.738    13799690.791     3209959.491    13799364.036
#Sta/Elev= 30
 1265.52    4.24 1342.97   14.31  2078.9   19.36 2219.61   18.06 2251.34    12.2
 2339.21   17.32 2970.36   15.12 3075.46   16.13 3165.26   24.78  3210.6   26.77
 3240.63   17.78 3311.83   15.35 4881.12   18.61  4925.1   15.69 4994.08   -3.55
 5022.41   -4.58  5097.3   16.77 5137.26   18.83 6364.81   15.66 6846.26   14.72
  7107.5    23.8 7158.48   15.43 7364.67    16.910090.48   15.2810146.21   15.53
10180.94   25.4810236.68   15.7510921.24   18.37 11057.1   11.4611264.13   15.51
#Mann= 6 ,-1 , 0
 1265.52     .07       0 3165.26     .12       0 4881.12    .032       0
 5137.26     .12       0 6364.81     .15       0 7364.67     .07       0
#XS Ineff= 2 ,-1
 1265.52 4846.42   18.92 5119.4511264.13   18.92
Permanent Ineff=
       F       F
#Block Obstruct= 3 ,-1
  586.48  4894.2   15.08 1182.82 3006.02   18.06 6372.9611409.46   16.81
Bank Sta=4881.12,5137.26
XS Rating Curve= 0
Exp/Cntr=.3,.1

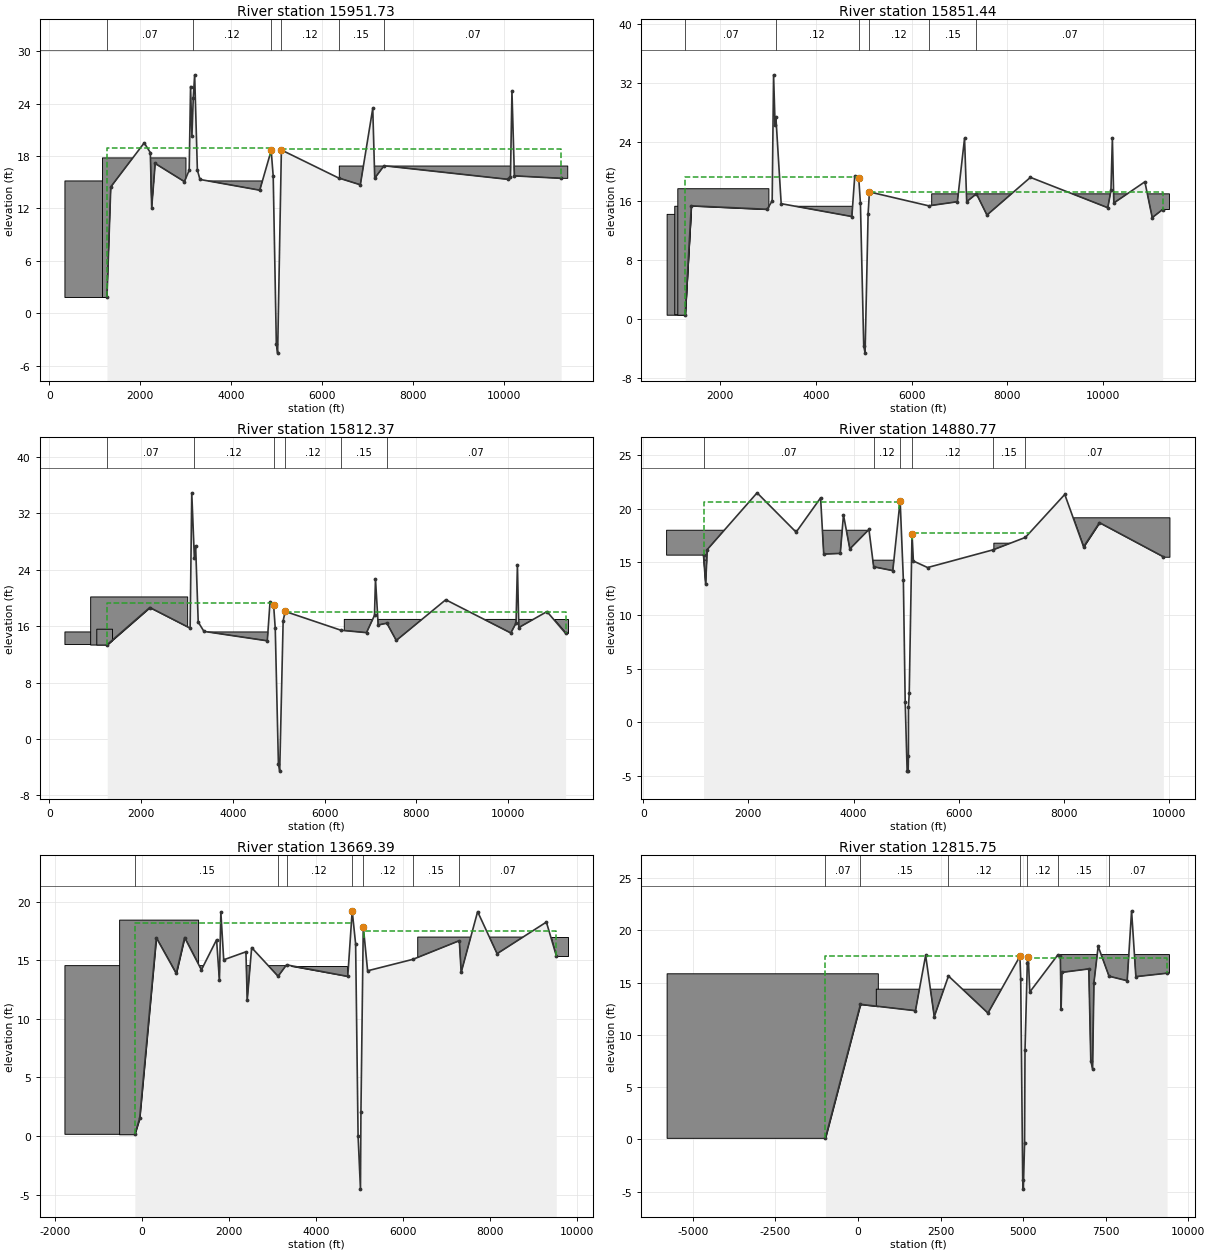
Type RM Length L Ch R = 1 ,15951.73,105.89,100.29,93.75
XS GIS Cut Line= 4
     3219944.287    13799863.653     3216311.713       13799705.
     3216118.625    13799680.824     3209960.021     13799354.05
#Sta/Elev= 30
 1265.78     1.8 1349.54   14.47 2084.69   19.51 2219.82    18.4 2249.85    12.1
 2327.11   17.15 2970.53   15.07 3075.63   16.39 3105.66   25.97 3135.69   20.27
 3165.38   24.69 3195.75   27.31 3255.81   16.39 3313.47   15.32 4628.87   14.09
 4880.52   18.64  4925.1   15.69 4994.08   -3.55 5022.41   -4.58    5105    18.7
 6364.71   15.49 6843.49   14.71 7116.72   23.46 7159.95   15.46  7364.5   16.89
10083.16   15.3410147.98   15.6210181.02   25.4110234.78   15.7311263.68   15.45
#Mann= 6 ,-1 , 0
 1265.78     .07       0 3165.38     .12       0 4880.52    .032       0
    5105     .12       0 6364.71     .15       0  7364.5     .07       0
#XS Ineff= 2 ,-1
 1265.78 4846.42   18.92 5133.1111263.68   18.78
Permanent Ineff=
       F       F
#Block Obstruct= 3 ,-1
  340.07 4858.29   15.15 1166.05 3004.83   17.79 6380.1711409.35   16.86
Bank Sta=4880.52,5105
XS Rating Curve= 0
Exp/Cntr=.3,.1

Type RM Length L Ch R = 1 ,15851.44,39.03,39.07,39.12
XS GIS Cut Line= 2
     3219954.796    13799790.094     3209975.409    13799261.723
#Sta/Elev= 30
 1262.48     .62 1390.94   15.36 2978.52   14.89 3083.01   16.03 3112.28   33.09
 3143.75   26.35 3161.22   27.32 3271.41   15.65    4751   13.91 4811.08   19.38
 4895.01   19.12  4930.1   15.69 4999.08   -3.55 5027.41   -4.58 5091.19   14.29
  5118.4   17.24  6359.1   15.36 6959.09   15.91  7109.3   24.49 7154.36   15.92
 7358.43   16.98 7578.36   14.11 8488.26   19.2110107.84    15.110173.59   17.44
10203.63   24.5510233.67   15.7410883.74   18.6111037.77   13.7611255.85   14.86
#Mann= 6 ,-1 , 0
 1262.48     .07       0 3161.22     .12       0 4895.01    .032       0
  5118.4     .12       0  6359.1     .15       0 7358.43     .07       0
#XS Ineff= 2 ,-1
 1262.48 4846.42   19.22 5133.1111255.85   17.22
Permanent Ineff=
       F       F
#Block Obstruct= 4 ,-1
  873.72 1665.53   14.27  1044.1 4784.98    15.3 1097.59 3003.88   17.74
 6421.6811397.99   16.98
Bank Sta=4895.01,5118.4
XS Rating Curve= 0
Exp/Cntr=.3,.1

Type RM Length L Ch R = 1 ,15812.37,1005.53,931.6,867.78
XS GIS Cut Line= 2
     3219954.796    13799751.564     3209977.521    13799221.779
#Sta/Elev= 30
 1263.25   13.39 2190.97   18.65 3069.43   15.72 3105.11   34.93  3161.6    25.7
  3188.9   27.42 3245.96   16.57 3370.99   15.26  4751.8   13.92 4811.88   19.48
 4889.35   19.01  4925.1   15.69 4994.08   -3.55 5022.41   -4.58  5097.3   16.77
 5142.35   18.09 6358.83   15.42 6914.84   15.08 7088.84   17.53 7110.11   22.71
 7169.32   16.17 7357.96   16.42 7563.68   13.97 8642.27   19.7510060.61   15.03
10174.42   16.4310204.46   24.7210234.51    15.810849.12   18.0711254.58   14.98
#Mann= 6 ,-1 , 0
 1263.25     .07       0  3161.6     .12       0 4889.35    .032       0
 5142.35     .12       0 6358.83     .15       0 7357.96     .07       0
#XS Ineff= 2 ,-1
 1263.25 4846.42   19.22 5160.4111254.58   18.06
Permanent Ineff=
       F       F
#Block Obstruct= 4 ,-1
  340.07 4842.05   15.18  890.39 3004.73   20.22 1023.89 1365.19   15.64
 6430.2411301.92   16.96
Bank Sta=4889.35,5142.35
XS Rating Curve= 0
Exp/Cntr=.3,.1

Type RM Length L Ch R = 1 ,14880.77,1295.28,1211.38,1135.21
XS GIS Cut Line= 4
     3220084.399    13798080.734     3216378.016    13798588.494
     3216159.829    13798647.567     3211411.277     13799215.84
#Sta/Elev= 30
 1145.86   15.64 1186.21   12.94 1216.98   16.16 2165.02   21.47 2908.08   17.79
 3373.54      21 3433.15   15.74 3748.18    15.8 3808.74   19.41 3929.87   16.22
 4293.23   18.04 4383.17   14.55 4747.43   14.19 4886.98   20.75 4948.42   13.34
 4983.12    1.93 5020.12   -4.57 5039.68   -4.54 5044.72   -3.19 5045.64    1.42
 5060.43    2.76 5113.02   17.66 5138.92   15.09 5409.21   14.48 6658.03   16.14
 7270.49    17.3 8019.61   21.32 8377.85   16.42  8680.3   18.68 9895.34   15.49
#Mann= 6 ,-1 , 0
 1145.86     .07       0 4383.17     .12       0 4886.98    .032       0
 5113.02     .12       0 6658.03     .15       0 7270.49     .07       0
#XS Ineff= 2 ,-1
 1145.86 4869.17   20.57 5119.45 7337.88   17.72
Permanent Ineff=
       F       F
#Block Obstruct= 4 ,-1
  443.69 4300.34   17.97   791.7 4848.58   15.17 6670.32 9010.74   16.76
 7679.1810011.38   19.18
Bank Sta=4886.98,5113.02
XS Rating Curve= 0
Exp/Cntr=.3,.1

Type RM Length L Ch R = 1 ,13669.39,871.32,853.64,809.54
BEGIN DESCRIPTION:
500 year blocked on left at basin boundary
END DESCRIPTION:
XS GIS Cut Line= 4
     3220290.083    13795518.514     3215644.687    13797573.307
     3215499.817    13797673.069     3211304.126    13799108.688
#Sta/Elev= 30
 -164.75     .14  -53.57     1.5  329.76   16.92  788.79   13.87  980.24   16.94
 1366.37   14.18 1714.83   16.75 1780.43   13.29 1813.24    19.1 1878.85   15.04
 2389.75   15.72 2420.11   11.61 2521.47   16.08 3129.83   13.63 3323.63   14.61
 4731.47   13.62 4833.04   19.22 4912.05    16.4 4968.52       0 5023.36   -4.54
 5034.17    2.03 5087.95   17.88 5187.48    14.1 6230.62   15.08 7296.51   16.67
 7338.93   13.96 7717.17   19.15 8164.69   15.56 9298.06   18.26  9525.2    15.4
#Mann= 7 ,-1 , 0
 -164.75     .15       0 3129.83     .07       0 3323.63     .12       0
 4833.04    .032       0 5087.95     .12       0 6230.62     .15       0
 7296.51     .07       0
#XS Ineff= 2 ,-1
 -164.75 4839.59   18.15 5112.63  9525.2   17.47
Permanent Ineff=
       F       F
#Block Obstruct= 3 ,-1
-1771.74 4722.18   14.54  -525.6  1290.1   18.47 6340.08 9789.47   16.98
Bank Sta=4833.04,5087.95
XS Rating Curve= 0
Exp/Cntr=.3,.1

Type RM Length L Ch R = 1 ,12815.75,812.97,812.69,732.22
BEGIN DESCRIPTION:
500 year blocked on left at basin boundary
END DESCRIPTION:
XS GIS Cut Line= 4
     3220397.688    13794153.268     3215170.427    13796859.993
     3215015.003    13796974.254     3211304.126      13799081.9
#Sta/Elev= 30
 -985.76     .14   73.14   12.92 1739.34   12.31 2047.83   17.61 2308.87   11.74
 2739.18   15.63 3935.79   12.08 4903.55   17.52 4927.13   15.39  4987.8   -3.93
 5007.27   -4.77 5044.23    -.35 5057.22    8.54 5127.23   16.89  5155.9   17.49
 5202.73    14.1 6050.23   17.65 6127.34    17.5 6151.35   12.47 6176.21   15.98
 6989.87   16.31 7050.06    7.52 7103.63    6.74 7145.12   14.99 7273.16   18.47
 7602.28   15.61 8152.08   15.18 8285.03   21.87 8415.12   15.57 9361.27    15.9
#Mann= 7 ,-1 , 0
 -985.76     .07       0   73.14     .15       0 2739.18     .12       0
 4903.55    .032       0 5127.23     .12       0 6050.23     .15       0
 7602.28     .07       0
#XS Ineff= 2 ,-1
 -985.76 4880.55   17.59 5139.93 9361.27   17.34
Permanent Ineff=
       F       F
#Block Obstruct= 3 ,-1
-5797.41  599.32   15.89   552.9 4784.98   14.37 6047.03 9431.93   17.68
Bank Sta=4903.55,5155.9
XS Rating Curve= 0
Exp/Cntr=.3,.1

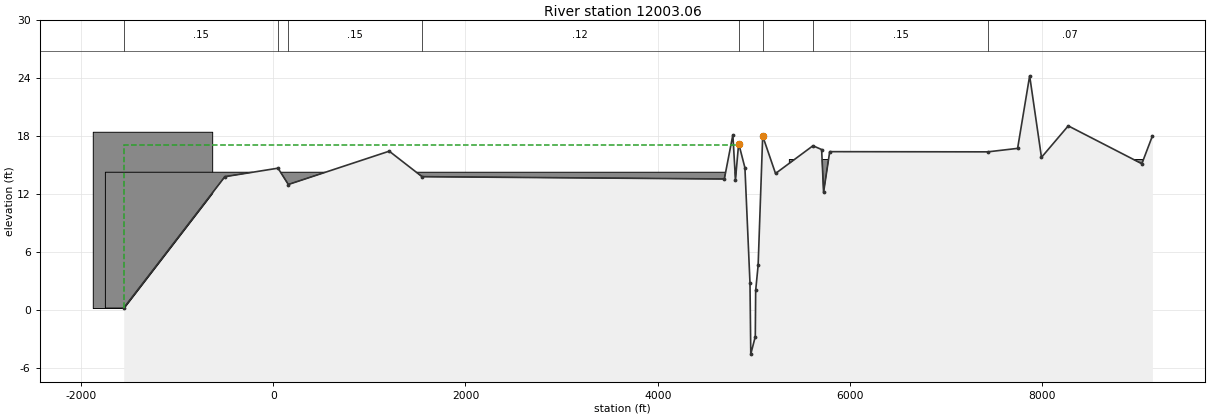
Type RM Length L Ch R = 1 ,12003.06,408.51,468.77,651.14
BEGIN DESCRIPTION:
500 year blocked on left at basin boundary
END DESCRIPTION:
XS GIS Cut Line= 4
     3220305.775    13793494.183      3214508.74    13796348.611
     3214436.703    13796518.787      3211250.55    13799028.324
#Sta/Elev= 30
-1555.13     .23    -503   13.83   50.21   14.71  157.23   13.02 1207.12   16.47
 1548.52   13.83 4693.31   13.59  4782.1   18.16 4809.12   13.53 4842.13   17.23
 4842.55   17.27  4907.6   14.75 4960.21    2.82 4968.55   -4.54  5015.5   -2.72
 5019.44    2.05 5045.01    4.66  5092.4   18.04 5225.97   14.16 5615.38   17.03
  5705.7   16.64 5725.86   12.21 5789.57   16.42 7434.76    16.4 7744.46   16.76
 7869.81   24.27  7992.8   15.83 8271.27   19.09 9036.95   15.17 9147.13   18.05
#Mann= 8 ,-1 , 0
-1555.13     .15       0   50.21     .12       0  157.23     .15       0
 1548.52     .12       0 4842.55    .032       0  5092.4     .12       0
 5615.38     .15       0 7434.76     .07       0
#XS Ineff= 1 ,-1
-1808.87 4853.24   17.09
Permanent Ineff=
       F
#Block Obstruct= 4 ,-1
-1877.13 -634.81   18.48-1745.94  4844.5   14.29   850.2 2518.22   12.52
  5369.8 9376.42   15.61
Bank Sta=4842.13,5092.4
XS Rating Curve= 0
Exp/Cntr=.3,.1