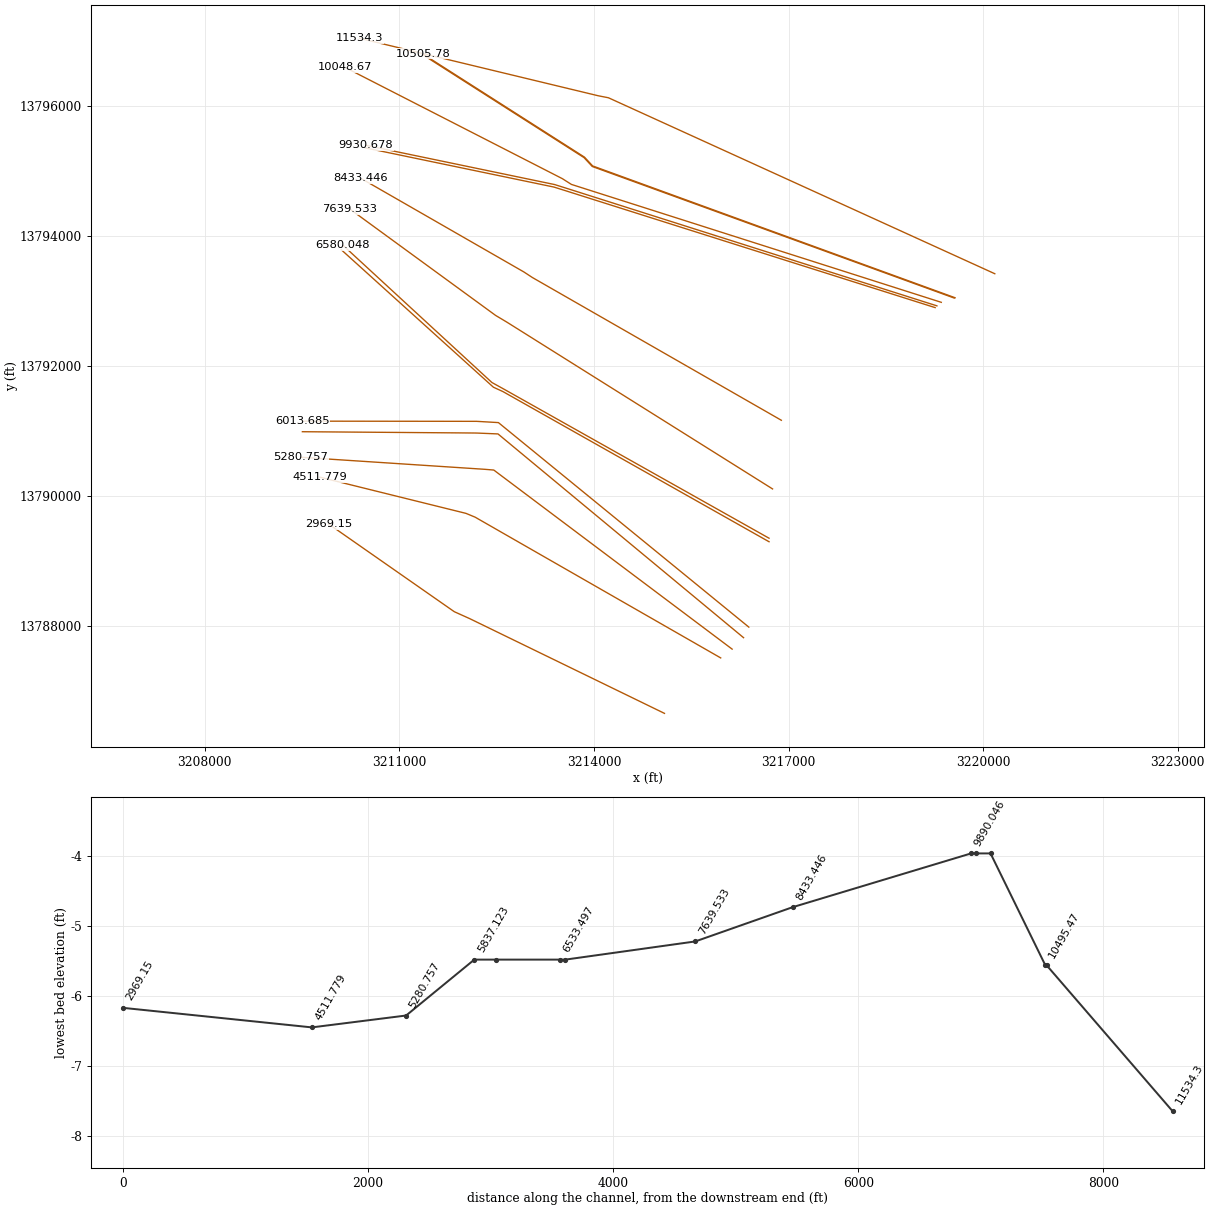
HEC-RAS study B106_00_00.prj: B106-00-00

--- B106_00_00.g03 (geometry) --- (continued)

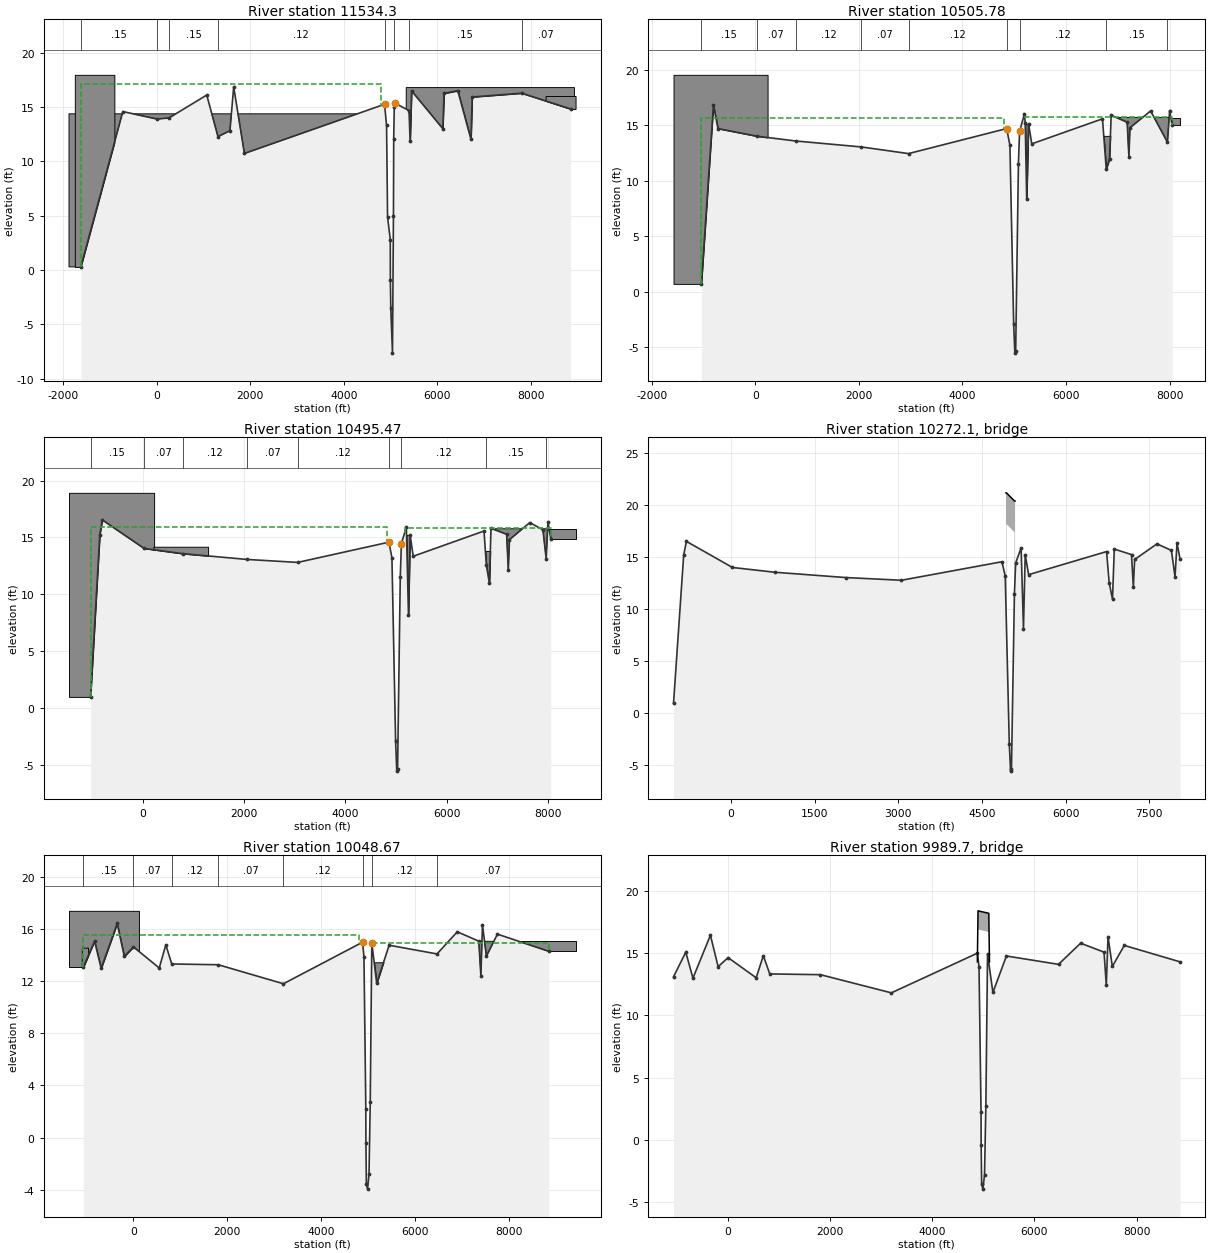
Type RM Length L Ch R = 1 ,11534.3 ,1067.9,1028.51,905.41
BEGIN DESCRIPTION:
500 year blocked on left at basin boundary
END DESCRIPTION:
XS GIS Cut Line= 4
     3220180.235    13793422.446     3214224.482    13796130.858
     3214062.755     13796162.72     3210390.879    13797045.883
#Sta/Elev= 30
-1625.95     .29 -726.94   14.59    3.17    13.9   261.2      14 1069.14   16.11
 1309.61   12.28 1565.27   12.82 1645.79   16.86 1875.18   10.73  4874.2   15.26
 4917.58   13.31 4939.28    4.87  4997.3     2.8 4998.84     -.9 5007.67   -3.47
 5044.34   -7.65 5064.78    4.98 5070.51   12.08 5082.42   14.99 5090.98   15.37
  5398.4   14.68 5421.55   11.85 5453.85   16.49 6122.01   13.01 6147.12   16.26
 6442.02   16.51 6724.28   12.02 6750.06   15.93 7809.74   16.28 8858.15   14.83
#Mann= 8 ,-1 , 0
-1625.95     .15       0    3.17     .12       0   261.2     .15       0
 1309.61     .12       0  4874.2    .032       0 5082.42     .12       0
  5398.4     .15       0 7809.74     .07       0
#XS Ineff= 1 ,-1
-1625.95 4798.63   17.09
Permanent Ineff=
       F
#Block Obstruct= 4 ,-1
-1879.04 4728.33   14.38-1754.27 -907.85   17.97 5327.51 8926.78   16.84
 8320.82 8962.46   16.02
Bank Sta=4874.2,5090.98
XS Rating Curve= 0
Exp/Cntr=.3,.1

Type RM Length L Ch R = 1 ,10505.78,10.23,10.32,10
BEGIN DESCRIPTION:
500 year blocked on left at basin boundary
END DESCRIPTION:
XS GIS Cut Line= 4
     3219568.228    13793052.551     3213980.467    13795081.686
     3213854.135    13795217.332     3211359.989    13796806.681
#Sta/Elev= 30
-1038.74     .69 -806.64   16.83 -719.06   14.71   33.72   14.02  778.79   13.59
 2051.06   13.05 2959.82   12.45 4854.66   14.71 4916.75   13.21 4989.32   -2.91
 5012.51   -5.56 5028.15   -5.37 5081.35   11.51 5103.25   14.46 5197.66   16.03
 5212.67   15.17 5241.12    8.33 5276.41   15.15 5339.08   13.33 6703.97   15.59
 6776.63   11.04 6839.79   11.99    6872   15.91 7180.72   15.28 7214.31   12.17
  7234.6   14.78  7632.9    16.3 7958.03   13.48 8000.09   16.33  8048.9   15.01
#Mann= 9 ,-1 , 0
-1038.74     .15       0   33.72     .07       0  778.79     .12       0
 2051.06     .07       0 2959.82     .12       0 4854.66    .032       0
 5103.25     .12       0 6776.63     .15       0 7958.03     .07       0
#XS Ineff= 2 ,-1
 5180.89  8048.9   15.76-1038.74 4812.29   15.63
Permanent Ineff=
       F       F
#Block Obstruct= 4 ,-1
-1576.79  238.91   19.56 5210.09 5276.31    15.1  6368.6 6941.98   14.05
 6910.06  8202.1    15.7
Bank Sta=4854.66,5103.25
XS Rating Curve= 0
Exp/Cntr=.5,.3

Type RM Length L Ch R = 1 ,10495.47,393.53,446.8,494.65
BEGIN DESCRIPTION:
500 year blocked on left at basin boundary
END DESCRIPTION:
XS GIS Cut Line= 4
     3219554.777    13793048.068      3213974.79    13795073.108
     3213847.686    13795209.584     3211354.615    13796798.248
#Sta/Elev= 30
-1028.33     .97 -845.89   15.24 -796.98   16.54   28.21   14.03  787.44   13.57
 2058.47   13.06 3057.14    12.8 4857.35   14.58 4916.75   13.21 4989.32   -2.91
 5012.51   -5.56 5028.15   -5.37 5081.35   11.51 5103.25   14.46 5201.45   15.91
 5243.45    8.14 5274.65   15.24 5336.58   13.34 6733.05   15.56 6779.45   12.56
 6839.16   10.98 6871.07    15.8 7179.92   15.27 7212.68   12.12 7235.96    14.8
 7636.27    16.3 7895.26   15.67  7959.7   13.13  7995.3   16.38 8050.48   14.83
#Mann= 9 ,-1 , 0
-1028.33     .15       0   28.21     .07       0  787.44     .12       0
 2058.47     .07       0 3057.14     .12       0 4857.35    .032       0
 5103.25     .12       0 6779.45     .15       0  7959.7     .07       0
#XS Ineff= 2 ,-1
-1028.33 4812.29   15.89 5167.24 8050.48   15.82
Permanent Ineff=
       F       F
#Block Obstruct= 5 ,-1
-1453.92  225.26   18.92   211.6  1290.1   14.18 5198.27 5274.82   15.21
  6709.9 6887.37    13.8 6955.63 8539.25   15.76
Bank Sta=4857.35,5103.25
XS Rating Curve= 0
Exp/Cntr=.5,.3

Type RM Length L Ch R = 3 ,10272.1 ,,,
BEGIN DESCRIPTION:
U shaped pipeline
END DESCRIPTION:
Bridge Culvert--1,0,-1,-1, 0
Deck Dist Width WeirC Skew NumUp NumDn MinLoCord MaxHiCord MaxSubmerge Is_Ogee
120,3,2.6,0, 6, 6, , , .95, 0, 0,0,,
    4930 4937.99    4938    5084 5084.01    5093
   21.21   21.21   21.21   20.42   20.42   20.42
       0       0   18.21   17.42       0       0
    4930 4937.99    4938    5084 5084.01    5093
   21.21   21.21   21.21   20.42   20.42   20.42
       0       0   18.21   17.42       0       0
Pier Skew, UpSta & Num, DnSta & Num=  ,4949.2, 2 ,4949.2, 2 , 0 , 0 , 0 ,,
    1.25    1.25
       0
    1.25    1.25
       0
Pier Skew, UpSta & Num, DnSta & Num=  ,4960.4, 2 ,4960.4, 2 , 0 , 0 , 0 ,,
     1.4     1.4
       0
     1.4     1.4
       0
Pier Skew, UpSta & Num, DnSta & Num=  ,4971.6, 2 ,4971.6, 2 , 0 , 0 , 0 ,,
     1.4     1.4
       0
     1.4     1.4
       0
Pier Skew, UpSta & Num, DnSta & Num=  ,4982.8, 2 ,4982.8, 2 , 0 , 0 , 0 ,,
     1.4     1.4
       0
     1.4     1.4
       0
Pier Skew, UpSta & Num, DnSta & Num=  ,4994, 2 ,4994, 2 , 0 , 0 , 0 ,,
     1.4     1.4
       0
     1.4     1.4
       0
Pier Skew, UpSta & Num, DnSta & Num=  ,5005.2, 2 ,5005.2, 2 , 0 , 0 , 0 ,,
     1.4     1.4
       0
     1.4     1.4
       0
Pier Skew, UpSta & Num, DnSta & Num=  ,5016.4, 2 ,5016.4, 2 , 0 , 0 , 0 ,,
     1.4     1.4
       0
     1.4     1.4
       0
Pier Skew, UpSta & Num, DnSta & Num=  ,5027.6, 2 ,5027.6, 2 , 0 , 0 , 0 ,,
     1.4     1.4
       0
     1.4     1.4
       0
Pier Skew, UpSta & Num, DnSta & Num=  ,5038.8, 2 ,5038.8, 2 , 0 , 0 , 0 ,,
     1.4     1.4
       0
     1.4     1.4
       0
Pier Skew, UpSta & Num, DnSta & Num=  ,5050, 2 ,5050, 2 , 0 , 0 , 0 ,,
     1.4     1.4
       0
     1.4     1.4
       0
Pier Skew, UpSta & Num, DnSta & Num=  ,5061.2, 2 ,5061.2, 2 , 0 , 0 , 0 ,,
     1.4     1.4
       0
     1.4     1.4
       0
Pier Skew, UpSta & Num, DnSta & Num=  ,5072.4, 2 ,5072.4, 2 , 0 , 0 , 0 ,,
    1.25    1.25
       0
    1.25    1.25
       0
BR Coef=-1 , 1 , 1 ,1.25, 0 ,,,.8,0,2,1,
WSPro=,,,, 1 ,,,, 0 ,,,, 0 ,,,,-1 ,-1 ,-1 , 0 , 0 , 0 , 0 , 0
BC Design=,, 0 ,, 0 ,,,,,,
BC HTab HWMax=16.54

Type RM Length L Ch R = 1 ,10048.67,93.46,118,192.53
BEGIN DESCRIPTION:
500 year blocked on left at basin boundary
END DESCRIPTION:
XS GIS Cut Line= 4
     3219355.488    13792982.222     3213653.452    13794797.057
     3213512.541    13794886.308     3210160.062    13796599.637
#Sta/Elev= 30
-1063.39    13.1 -823.54   15.08 -683.31   12.99 -340.97   16.44 -190.22   13.91
    4.91   14.64  554.79   13.02  694.61    14.8  820.57   13.33 1812.13   13.27
 3200.32   11.81  4885.8      15  4916.6   13.87  4956.1    2.21 4958.18    -.38
 4967.97   -3.57 4992.94   -3.96 5024.08   -2.81 5050.39    2.74  5083.4   14.94
 5188.15   11.84 5452.81   14.77 6472.46    14.1 6905.23    15.8 7363.28   15.08
 7407.89   12.43 7441.58   16.33 7525.81   13.93 7760.25   15.62 8852.21    14.3
#Mann= 8 ,-1 , 0
-1063.39     .15       0    4.91     .07       0  820.57     .12       0
 1812.13     .07       0 3200.32     .12       0  4885.8    .032       0
  5083.4     .12       0 6472.46     .07       0
#XS Ineff= 2 ,-1
-1063.39 4812.29   15.52  5084.7 8852.21   14.97
Permanent Ineff=
       F       F
#Block Obstruct= 4 ,-1
-1368.42  121.46   17.41-1096.09 -961.85   14.58 5112.63 5399.32   13.46
 7319.59 9424.98   15.07
Bank Sta=4885.8,5083.4
XS Rating Curve= 0
Exp/Cntr=.5,.3

Type RM Length L Ch R = 3 ,9989.7  ,,,
BEGIN DESCRIPTION:
Pipeline Structure
END DESCRIPTION:
Bridge Culvert--1,0,-1,-1, 0
Deck Dist Width WeirC Skew NumUp NumDn MinLoCord MaxHiCord MaxSubmerge Is_Ogee
74,1.5,2.6,0, 4, 4, , , .95, 0, 0,0,,
    4884    4897    5108    5121
    14.3    18.4    18.2    14.3
    12.8    16.9    16.7    12.8
    4884    4897    5108    5121
    14.3    18.4    18.2    14.3
    12.8    16.9    16.7    12.8
Pier Skew, UpSta & Num, DnSta & Num=  ,4893, 2 ,4893, 2 , 0 , 0 , 0 ,,
       1       1
       0
       1       1
       0
Pier Skew, UpSta & Num, DnSta & Num=  ,4904, 2 ,4904, 2 , 0 , 0 , 0 ,,
    1.25    1.25
       0
    1.25    1.25
       0
Pier Skew, UpSta & Num, DnSta & Num=  ,4928, 2 ,4928, 2 , 0 , 0 , 0 ,,
    1.25    1.25
       0
    1.25    1.25
       0
Pier Skew, UpSta & Num, DnSta & Num=  ,4958, 2 ,4958, 2 , 0 , 0 , 0 ,,
    1.25    1.25
       0
    1.25    1.25
       0
Pier Skew, UpSta & Num, DnSta & Num=  ,4990, 2 ,4990, 2 , 0 , 0 , 0 ,,
    1.25    1.25
       0
    1.25    1.25
       0
Pier Skew, UpSta & Num, DnSta & Num=  ,5018, 2 ,5018, 2 , 0 , 0 , 0 ,,
    1.25    1.25
       0
    1.25    1.25
       0
Pier Skew, UpSta & Num, DnSta & Num=  ,5050, 2 ,5050, 2 , 0 , 0 , 0 ,,
    1.25    1.25
       0
    1.25    1.25
       0
Pier Skew, UpSta & Num, DnSta & Num=  ,5080, 2 ,5080, 2 , 0 , 0 , 0 ,,
    1.25    1.25
       0
    1.25    1.25
       0
Pier Skew, UpSta & Num, DnSta & Num=  ,5100, 2 ,5100, 2 , 0 , 0 , 0 ,,
    1.25    1.25
       0
    1.25    1.25
       0
Pier Skew, UpSta & Num, DnSta & Num=  ,5113, 2 ,5113, 2 , 0 , 0 , 0 ,,
       1       1
       0
       1       1
       0
BR Coef=-1 , 1 , 1 ,1.25, 0 ,,,.8,-1,2,1,
WSPro=,,,, 1 ,,,, 0 ,,,, 0 ,,,,-1 ,-1 ,-1 , 0 , 0 , 0 , 0 , 0
BC Design=,, 0 ,, 0 ,,,,,,
BC HTab HWMax=16.44

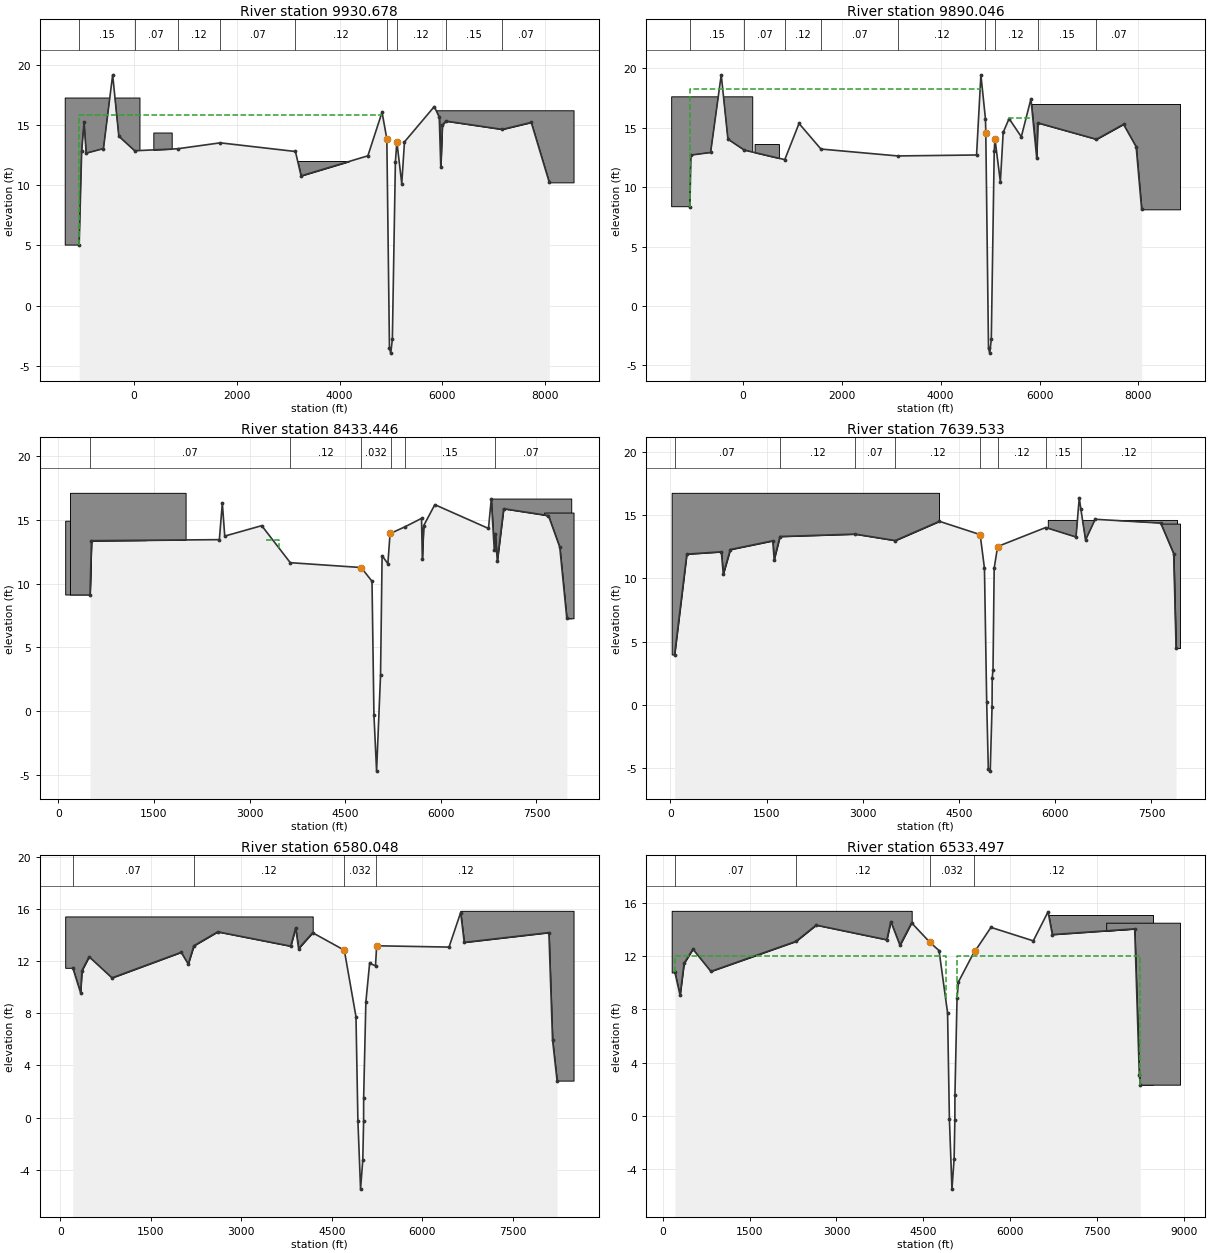
Type RM Length L Ch R = 1 ,9930.678,47.31,40.63,41.57
BEGIN DESCRIPTION:
500 year blocked on left at basin boundary
END DESCRIPTION:
XS GIS Cut Line= 4
     3219287.743    13792928.026       3213598.1     13794731.12
     3213393.663    13794795.258     3210483.206     13795399.39
#Sta/Elev= 30
-1069.95    5.03-1021.83   12.83 -974.62   15.29 -932.95   12.68 -597.52   13.06
 -417.79    19.2 -297.63   14.09   10.89   12.88  852.67   13.05 1676.64   13.54
 3141.49   12.82 3251.56   10.79  4552.3   12.46 4828.39   16.09  4921.6   13.87
 4972.97   -3.57 4997.94   -3.96 5029.08   -2.81  5088.4   11.95    5117   13.63
 5212.35   10.14 5265.25   13.62 5846.01   16.56 5942.66   15.67 5972.57    11.5
 6003.21   15.02 6071.17   15.35 7169.81   14.66 7734.22   15.24 8085.33   10.25
#Mann= 9 ,-1 , 0
-1069.95     .15       0   10.89     .07       0  852.67     .12       0
 1676.64     .07       0 3141.49     .12       0  4921.6    .032       0
    5117     .12       0 6071.17     .15       0 7169.81     .07       0
#XS Ineff= 1 ,-1
-1781.57 4825.94   15.83
Permanent Ineff=
       F
#Block Obstruct= 4 ,-1
-1342.12  114.18   17.27  373.96  731.73    14.4 2323.89 4186.23   12.03
 5848.14  8557.7   16.25
Bank Sta=4921.6,5117
XS Rating Curve= 0
Exp/Cntr=.5,.3

Type RM Length L Ch R = 1 ,9890.046,1535.07,1456.6,1365.55
BEGIN DESCRIPTION:
500 year blocked on left at basin boundary
END DESCRIPTION:
XS GIS Cut Line= 4
     3219260.646    13792900.928      3213586.06    13794692.975
     3213383.586    13794756.497     3210475.076    13795360.225
#Sta/Elev= 30
-1069.24    8.35-1049.42   12.69 -650.97   12.91 -435.89   19.44 -300.35   14.03
   30.13   13.11   848.8   12.31 1136.95   15.35 1579.49    13.2 3132.19   12.62
 4726.47    12.7 4814.02   19.43 4906.59   15.72    4913   14.55 4967.97   -3.57
 4992.94   -3.96 5024.08   -2.81  5083.4      13    5098   14.07 5207.89   10.44
 5264.53    14.6 5383.95   15.76 5631.06   14.23 5825.72   17.41 5943.24   12.43
 5963.59    15.4 7150.95   14.02 7697.25   15.28 7953.23   13.39  8064.3    8.13
#Mann= 9 ,-1 , 0
-1069.24     .15       0   30.13     .07       0   848.8     .12       0
 1579.49     .07       0 3132.19     .12       0 4906.59    .032       0
    5098     .12       0 5963.59     .15       0 7150.95     .07       0
#XS Ineff= 2 ,-1
-1069.24 4825.94   18.21 5385.67 5822.53   15.83
Permanent Ineff=
       F       F
#Block Obstruct= 3 ,-1
-1438.01  201.09   17.59  238.91  730.38   13.62 5822.53 8839.59   16.99
Bank Sta=4913,5098
XS Rating Curve= 0
Exp/Cntr=.3,.1

Type RM Length L Ch R = 1 ,8433.446,800.99,793.91,779.51
XS GIS Cut Line= 4
      3216889.59    13791166.671     3213052.066    13793363.662
      3212919.47    13793450.185     3210406.267    13794891.593
#Sta/Elev= 30
  498.57    9.15  521.16   13.38 2526.78   13.46 2573.33   16.33 2611.32   13.74
 3191.24   14.56  3639.1   11.65  4750.9   11.27 4920.84   10.19 4951.04     -.3
 4992.61   -4.73 5054.66    2.82 5079.16    12.2 5169.66   11.57 5205.04   14.02
 5218.56   13.97 5433.69   14.46 5697.28   15.13 5710.09   11.94 5731.11   14.56
 5906.08   16.21 6747.61   14.34 6790.76   16.62 6839.46   12.61 6854.41   13.88
 6885.94   11.79 6985.62   15.89 7687.88   15.35 7865.54   12.87 7976.03    7.28
#Mann= 6 ,-1 , 0
  498.57     .07       0  3639.1     .12       0  4750.9    .032       0
 5218.56     .12       0 5433.69     .15       0 6854.41     .07       0
#XS Ineff= 1 ,-1
 3257.75 3461.85    13.4
Permanent Ineff=
       F
#Block Obstruct= 6 ,-1
  109.22 1374.29   14.95  183.54  1997.3   17.14 5646.42 5819.16    14.4
 6789.53 8045.51   16.69 7599.54 7881.68   15.45 7620.78 8081.39   15.59
Bank Sta=4750.9,5205.04
XS Rating Curve= 0
Exp/Cntr=.3,.1

Type RM Length L Ch R = 1 ,7639.533,1045.66,1059.48,998.38
BEGIN DESCRIPTION:
500 year blocked on left at basin boundary
END DESCRIPTION:
XS GIS Cut Line= 4
     3216754.101    13790109.858     3212661.248    13792675.176
     3212484.787    13792780.542     3210237.087    13794418.404
#Sta/Elev= 30
   67.46    3.99   257.3   11.92  795.91    12.1  825.95   10.34  935.37   12.28
 1596.93   12.97 1619.36   11.49 1709.03   13.31 2881.59    13.5 3506.95   12.99
 4194.86   14.51 4830.41   13.46 4897.24    10.8 4932.22     .23 4957.39   -5.04
 4987.17   -5.22 5015.54    -.16 5018.17    2.14 5030.61     2.8 5048.69    10.8
 5102.76   12.52 5852.05   14.02  6324.4   13.27 6375.21   16.37 6399.25    15.5
 6473.42   13.04 6623.61   14.67 7645.11   14.37 7847.13   11.96 7884.48     4.5
#Mann= 8 ,-1 , 0
   67.46     .07       0 1709.03     .12       0 2881.59     .07       0
 3506.95     .12       0 4830.41    .032       0 5102.76     .12       0
 5852.05     .15       0 6399.25     .12       0
#Block Obstruct= 3 ,-1
    21.6 4189.23   16.76 5892.34 7906.88   14.58 7645.05 7945.39   14.33
Bank Sta=4830.41,5102.76
XS Rating Curve= 0
Exp/Cntr=.3,.1

Type RM Length L Ch R = 1 ,6580.048,40.57,46.55,63.8
XS GIS Cut Line= 4
     3216699.906     13789351.12     3212616.849    13791643.375
     3212427.483    13791747.877     3210128.696    13793862.899
#Sta/Elev= 30
  206.54   11.49  336.17    9.57  358.65   11.28  477.33   12.34  856.42   10.72
 2001.67   12.68 2119.39   11.78 2212.17   13.18 2607.34   14.25 3816.74   13.15
 3898.99   14.55 3947.29   12.97 4180.09   14.18 4705.02   12.84 4898.17    7.74
 4929.89    -.22  4974.1   -5.48 5011.21   -3.21 5024.28    -.28  5025.2    1.54
 5061.83    8.86 5124.13   11.84 5221.66   11.64 5240.37   13.18 6439.31   13.08
 6632.39   15.73 6691.34   13.44 8094.07   14.19 8153.94    5.98 8229.06    2.84
#Mann= 4 ,-1 , 0
  206.54     .07       0 2212.17     .12       0 4705.02    .032       0
 5221.66     .12       0
#Block Obstruct= 2 ,-1
   81.23 4181.18   15.43 6626.18 8502.02   15.86
Bank Sta=4705.02,5240.37
XS Rating Curve= 0
Exp/Cntr=.5,.3

Type RM Length L Ch R = 1 ,6533.497,527.99,519.81,727.61
XS GIS Cut Line= 4
     3216699.906    13789296.924     3212598.669    13791607.707
     3212449.908    13791675.913     3210101.598    13793795.155
#Sta/Elev= 30
  211.58   10.76  300.44    9.05  369.33   11.44  522.05   12.51  832.29   10.84
 2300.49   13.09 2649.31   14.31 3869.52   13.21 3938.26   14.58  4096.3    12.8
 4297.33   14.48 4615.05   13.01 4771.13    12.4 4918.17    7.74 4949.89    -.22
  4994.1   -5.48 5031.21   -3.21 5044.28    -.28  5045.2    1.54 5081.83    8.86
 5106.91   10.06 5379.64   12.32 5393.06   12.36 5667.01   14.14 6398.01   13.13
 6652.97   15.31 6726.17    13.6  8148.6   14.03 8228.67    3.07 8245.85    2.35
#Mann= 4 ,-1 , 0
  211.58     .07       0 2300.49     .12       0 4615.05    .032       0
 5379.64     .12       0
#XS Ineff= 2 , 0
       0    4885      12 5081.83       0      12
Permanent Ineff=
       F       F
#Block Obstruct= 3 ,-1
  155.53 4298.83   15.38 6655.29 8464.16   15.07 7656.43  8930.6   14.49
Bank Sta=4615.05,5393.06
XS Rating Curve= 0
Exp/Cntr=.5,.3

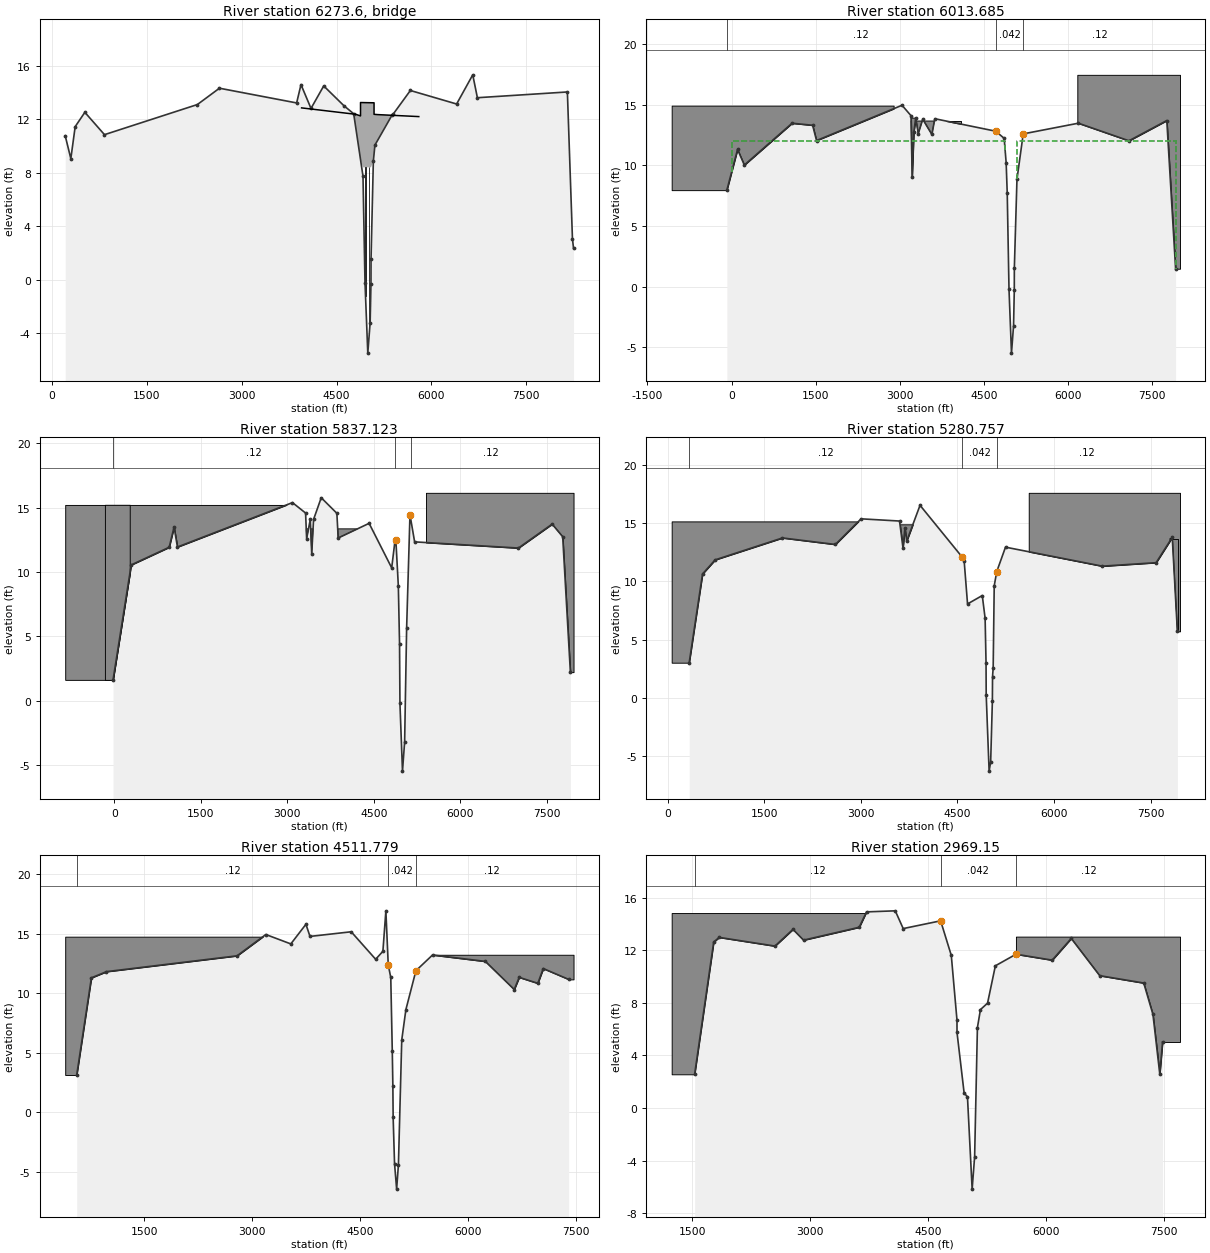
Type RM Length L Ch R = 3 ,6273.6  ,,,
BEGIN DESCRIPTION:
Red Bluff
END DESCRIPTION:
Bridge Culvert--1,0,-1,-1, 0
Deck Dist Width WeirC Skew NumUp NumDn MinLoCord MaxHiCord MaxSubmerge Is_Ogee
93,310,2.6,0, 8, 8, , , .95, 0, 0,0,,
    3948    4805 4878.99    4879    5093 5093.01    5144    5800
   12.84   12.36   12.24   13.24   13.22   12.36   12.34   12.19
                       0     8.4     8.4       0
    3948    4805 4878.99    4879    5093 5093.01    5144    5800
   12.84   12.36   12.24   13.24   13.22   12.36   12.34   12.19
                       0     8.4     8.4       0
Pier Skew, UpSta & Num, DnSta & Num=  ,4958, 4 ,4958, 4 , 3 , 3 , 0 ,,
     1.4     1.4     2.8     2.8
       0    5.59    5.59     8.5
     1.4     1.4     2.8     2.8
       0    5.59    5.59     8.5
Pier Skew, UpSta & Num, DnSta & Num=  ,5017, 4 ,5017, 4 , 3 , 3 , 0 ,,
     1.4     1.4     2.8     2.8
       0    5.59    5.59     8.5
     1.4     1.4     2.8     2.8
       0    5.59    5.59     8.5
BR Coef=-1 , 1 , 0 ,, 0 ,,,.8,0,2,0,
WSPro=,,,, 1 ,,,, 0 ,,,, 0 ,,,,-1 ,-1 ,-1 , 0 , 0 , 0 , 0 , 0
BC Design=,, 0 ,, 0 ,,,,,,
BC HTab HWMax=15.31

Type RM Length L Ch R = 1 ,6013.685,181.05,176.56,179.49
BEGIN DESCRIPTION:
500 year blocked on right at basin boundary
END DESCRIPTION:
XS GIS Cut Line= 4
     3216388.282    13787982.682     3212527.619    13791130.912
      3212191.68    13791150.293     3209505.447    13791153.122
#Sta/Elev= 30
  -82.73    7.96  107.98   11.32   228.9   10.03  1080.6   13.48 1447.08   13.31
 1516.82   12.05 3041.93   14.96  3201.9    14.1 3222.62    9.08 3252.14   12.75
 3286.59   13.93 3331.72   12.62 3411.31   13.81 3574.44   12.55 3626.83   13.85
 4713.49   12.82 4863.76   12.23 4898.84   10.24 4918.17    7.74 4949.89    -.22
  4994.1   -5.48 5031.21   -3.21 5044.28    -.28  5045.2    1.54    5092    8.86
 5203.66    12.6 6186.74   13.48 7089.19   12.03 7764.62    13.7 7921.58    1.48
#Mann= 3 , 0 , 0
  -82.73     .12       0 4713.49    .042       0 5203.66     .12       0
#XS Ineff= 2 , 0
       0    4885      12    5092       0      12
Permanent Ineff=
       F       F
#Block Obstruct= 4 ,-1
-1067.12 2891.92   14.93 2871.79 4086.37   13.66 3150.92 3287.14   13.94
 6168.37    8000   17.47
Bank Sta=4713.49,5203.66
XS Rating Curve= 0
Exp/Cntr=.5,.3

Type RM Length L Ch R = 1 ,5837.123,568.44,556.37,545.21
BEGIN DESCRIPTION:
500 year blocked on right at basin boundary
END DESCRIPTION:
XS GIS Cut Line= 4
     3216306.988    13787820.096     3212521.159    13790956.482
     3212185.982    13790970.323     3209505.447    13790990.535
#Sta/Elev= 30
  -21.15    1.61  294.07   10.54  952.68   11.91 1037.35   13.49 1095.79   11.93
  3090.8   15.38  3318.4   14.57 3336.66   12.59 3400.15   14.08 3424.66   11.41
 3456.61   14.07 3589.74   15.76 3861.01   14.55 3883.77   12.63 4420.08   13.77
 4811.93   10.31 4867.21   12.35 4884.14   12.47    4927    8.91    4948    4.43
 4954.89    -.22  4999.1   -5.48 5036.21   -3.21 5071.04    5.65 5128.93   14.44
 5209.65   12.33 7009.62   11.85 7595.02   13.71 7777.71   12.73 7911.16    2.21
#Mann= 3 ,-1 , 0
  -21.15     .12       0 4867.21    .042       0 5139.79     .12       0
#Block Obstruct= 4 ,-1
 -850.97  3096.7    15.2 -162.38  268.27   15.21 3182.19 4315.79   13.34
 5406.14 7965.87   16.14
Bank Sta=4884.14,5128.93
XS Rating Curve= 0
Exp/Cntr=.3,.1

Type RM Length L Ch R = 1 ,5280.757,743.51,768.98,706.96
BEGIN DESCRIPTION:
500 year blocked on right at basin boundary
END DESCRIPTION:
XS GIS Cut Line= 4
     3216130.853     13787643.96     3212456.374    13790400.444
     3212315.482    13790411.925     3209478.349    13790597.618
#Sta/Elev= 30
  335.72    3.02  542.74   10.63  738.36   11.84 1783.44   13.72 2604.91   13.16
 3003.97   15.36 3600.99   15.17 3654.09   12.88 3684.72   14.56 3711.14   13.44
 3919.09   16.52 4572.97   12.08 4603.62   11.78 4656.45    8.06  4885.2    8.78
 4929.32    6.83 4943.62    3.03 4946.11     .25  4991.4   -6.28 5015.42   -5.49
 5042.08    -.25 5044.52    1.83 5054.48    2.58 5070.68    9.61 5109.67   10.83
 5245.74   12.93 6748.91    11.3 7584.24    11.6 7834.26   13.77 7913.76    5.71
#Mann= 3 , 0 , 0
  335.72     .12       0 4572.97    .042       0 5109.67     .12       0
#Block Obstruct= 5 ,-1
   63.71 3030.72   15.14 3465.59 3832.66   14.89 5311.75 7935.21   12.39
 5606.37 7954.49   17.59 7799.77 7918.09   13.67
Bank Sta=4572.97,5109.67
XS Rating Curve= 0
Exp/Cntr=.3,.1

Type RM Length L Ch R = 1 ,4511.779,1526.98,1542.63,1457.27
BEGIN DESCRIPTION:
500 year blocked on right at basin boundary
END DESCRIPTION:
XS GIS Cut Line= 4
     3215954.717    13787508.471     3212168.577    13789675.272
     3212027.648    13789733.577     3209775.368    13790290.646
#Sta/Elev= 30
  560.67    3.14  764.34    11.3   973.7   11.82 2788.04   13.15 3187.96   14.94
 3535.08   14.15 3745.01    15.8 3801.51   14.78 4374.08   15.17 4713.78   12.86
 4814.44   13.53 4855.74   16.93 4888.72   12.38 4923.74   11.33 4944.68    5.17
 4952.83    2.24 4956.77    -.42 4976.16   -4.31  5005.3   -6.45 5030.16   -4.39
 5076.26    6.08  5134.1    8.64 5273.36    11.9  5504.1   13.22 6237.91   12.68
 6639.12   10.32 6708.19   11.34 6966.79   10.84 7042.34   12.08 7395.67   11.17
#Mann= 3 , 0 , 0
  560.67     .12       0 4888.72    .042       0 5273.36     .12       0
#Block Obstruct= 2 ,-1
  400.46 3203.64   14.76 5515.36 7463.03   13.24
Bank Sta=4888.72,5273.36
XS Rating Curve= 0
Exp/Cntr=.3,.1

Type RM Length L Ch R = 1 ,2969.15 ,3431.29,2969.15,2533.7
BEGIN DESCRIPTION:
500 year blocked on right at basin boundary
END DESCRIPTION:
XS GIS Cut Line= 4
     3215087.588    13786654.891     3212084.221    13788113.691
     3211847.194    13788220.147     3209913.858     13789567.42
#Sta/Elev= 30
 1531.09    2.56  1773.9   12.62 1843.38   12.97 2553.05   12.31 2782.41   13.58
 2917.13   12.76 3625.74   13.74 3718.38   14.91 4084.34   14.99 4185.48   13.64
 4661.85   14.23 4797.45    11.6    4870    6.67 4870.08    5.75 4961.01    1.13
 5003.28     .85  5062.8   -6.17 5094.48    -3.7 5129.92    6.11 5168.52    7.48
 5258.83    7.97 5358.44   10.81 5621.23   11.69 6081.55   11.24 6324.21   12.89
 6686.36   10.06 7246.63     9.5 7363.82    7.11 7450.83    2.58  7486.3    5.02
#Mann= 3 , 0 , 0
 1531.09     .12       0 4661.85    .042       0 5621.23     .12       0
#Block Obstruct= 2 ,-1
 1238.91 3731.51   14.82 5620.14 7708.09   13.03
Bank Sta=4661.85,5621.23
XS Rating Curve= 0
Exp/Cntr=.3,.1

Chan Stop Cuts=-1

--- B106_00_00.g02 (geometry) ---

Geom Title=B106-00-00 June 2007
Version=Version 3.0.1  Mar 2001

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
River Reach=B106-00-00      ,B106-00-00_0030

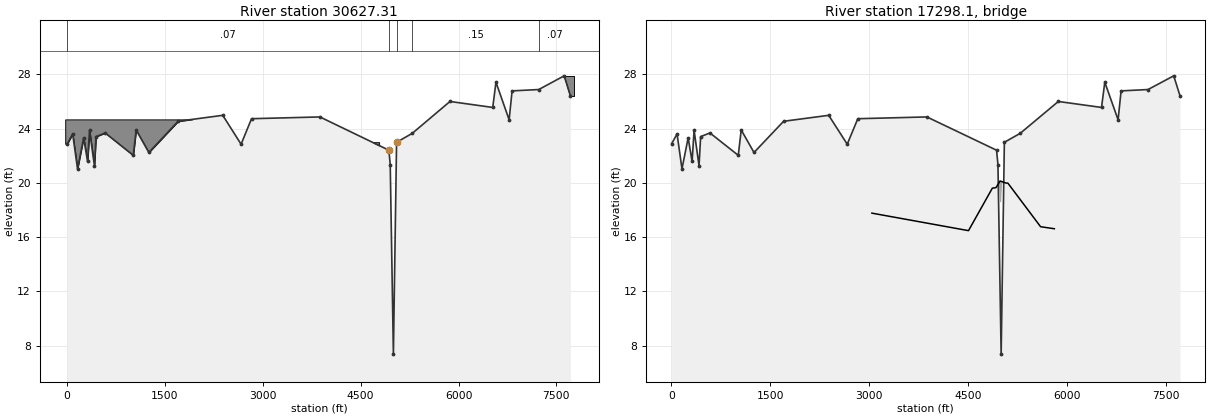
Type RM Length L Ch R = 1 ,30627.31,1036.43,1037.3,1037.12
XS GIS Cut Line= 4
 3218265.447402113814068.7240062     3213330.308    13813757.546
     3213234.198    13813742.058     3210568.619    13813664.363
#Sta/Elev= 30
    5.38   22.89   87.15   23.61  161.64   21.03  255.18   23.32  315.29   21.58
  345.35   23.87   420.5   21.26  444.62   23.41  585.83   23.68 1015.62   22.03
 1059.97    23.9 1253.98   22.24 1702.92   24.54 2386.93   24.98 2667.97   22.85
 2828.24   24.73    3876   24.864932.422 22.40894953.463  21.3535002.092  7.3796
5050.814 22.9917 5290.82   23.65 5869.18      26  6524.4   25.56 6573.93   27.42
 6775.67   24.65 6820.99   26.78 7229.68   26.88 7619.14   27.89 7714.39   26.42
#Mann= 5 ,-1 , 0
    5.38     .07       04932.422    .032       05050.814     .15       0
 5290.82     .15       0 7229.68     .07       0
#Block Obstruct= 3 ,-1
   -27.3 2102.39   24.68 4695.16 4783.31      23 7613.31 7762.59   27.88
Bank Sta=4932.422,5050.814
XS Rating Curve= 0
Exp/Cntr=.3,.1

Type RM Length L Ch R = 3 ,17298.1 ,,,
BEGIN DESCRIPTION:
Big Island Slough Railroad Crossing
END DESCRIPTION:
Bridge Culvert--1,0,-1,-1, 0
Deck Dist Width WeirC Skew NumUp NumDn MinLoCord MaxHiCord MaxSubmerge Is_Ogee
102,17,2.6,0, 11, 11, , , .95, 0, 0,0,,
    3042    4507 4868.48    4924 4924.01 4985.31 5073.99    5074  5104.3    5600
    5809
   17.77   16.48   19.61   19.65   19.65   20.14   19.99   19.99   19.98   16.77
   16.62
                       0       0   18.58   18.58   18.58       0       0
        
    3042    4507 4868.48    4924 4924.01 4985.31 5073.99    5074  5104.3    5600
    5809
   17.77   16.48   19.61   19.65   19.65   20.14   19.99   19.99   19.98   16.77
   16.62
                       0       0   18.58   18.58   18.58       0       0
        
Pier Skew, UpSta & Num, DnSta & Num=  ,4952, 4 ,4952, 4 , 3 , 3 , 0 ,,
     1.4     1.4     2.8     2.8
       0   15.76   15.76
     1.4     1.4     2.8     2.8
       0   15.76   15.76
Pier Skew, UpSta & Num, DnSta & Num=  ,4982.175, 4 ,4982.175, 4 , 3 , 3 , 0 ,,
     1.4     1.4     2.8     2.8
       0   15.76   15.76
     1.4     1.4     2.8     2.8
       0   15.76   15.76
Pier Skew, UpSta & Num, DnSta & Num=  ,5012.061, 4 ,5012.061, 4 , 3 , 3 , 0 ,,
     1.4     1.4     2.8     2.8
       0   15.76   15.76
     1.4     1.4     2.8     2.8
       0   15.76   15.76
Pier Skew, UpSta & Num, DnSta & Num=  ,5041.93, 4 ,5041.93, 4 , 3 , 3 , 0 ,,
     1.4     1.4     2.8     2.8
       0   15.76   15.76
     1.4     1.4     2.8     2.8
       0   15.76   15.76
BR Coef=-1 , 1 , 1 ,1.25, 0 ,,,.8,0,1.2,0,
WSPro=,,,, 1 ,,,, 0 ,,,, 0 ,,,,-1 ,-1 ,-1 , 0 , 0 , 0 , 0 , 0
BC Design=,, 0 ,, 0 ,,,,,,
BC HTab HWMax=20.36